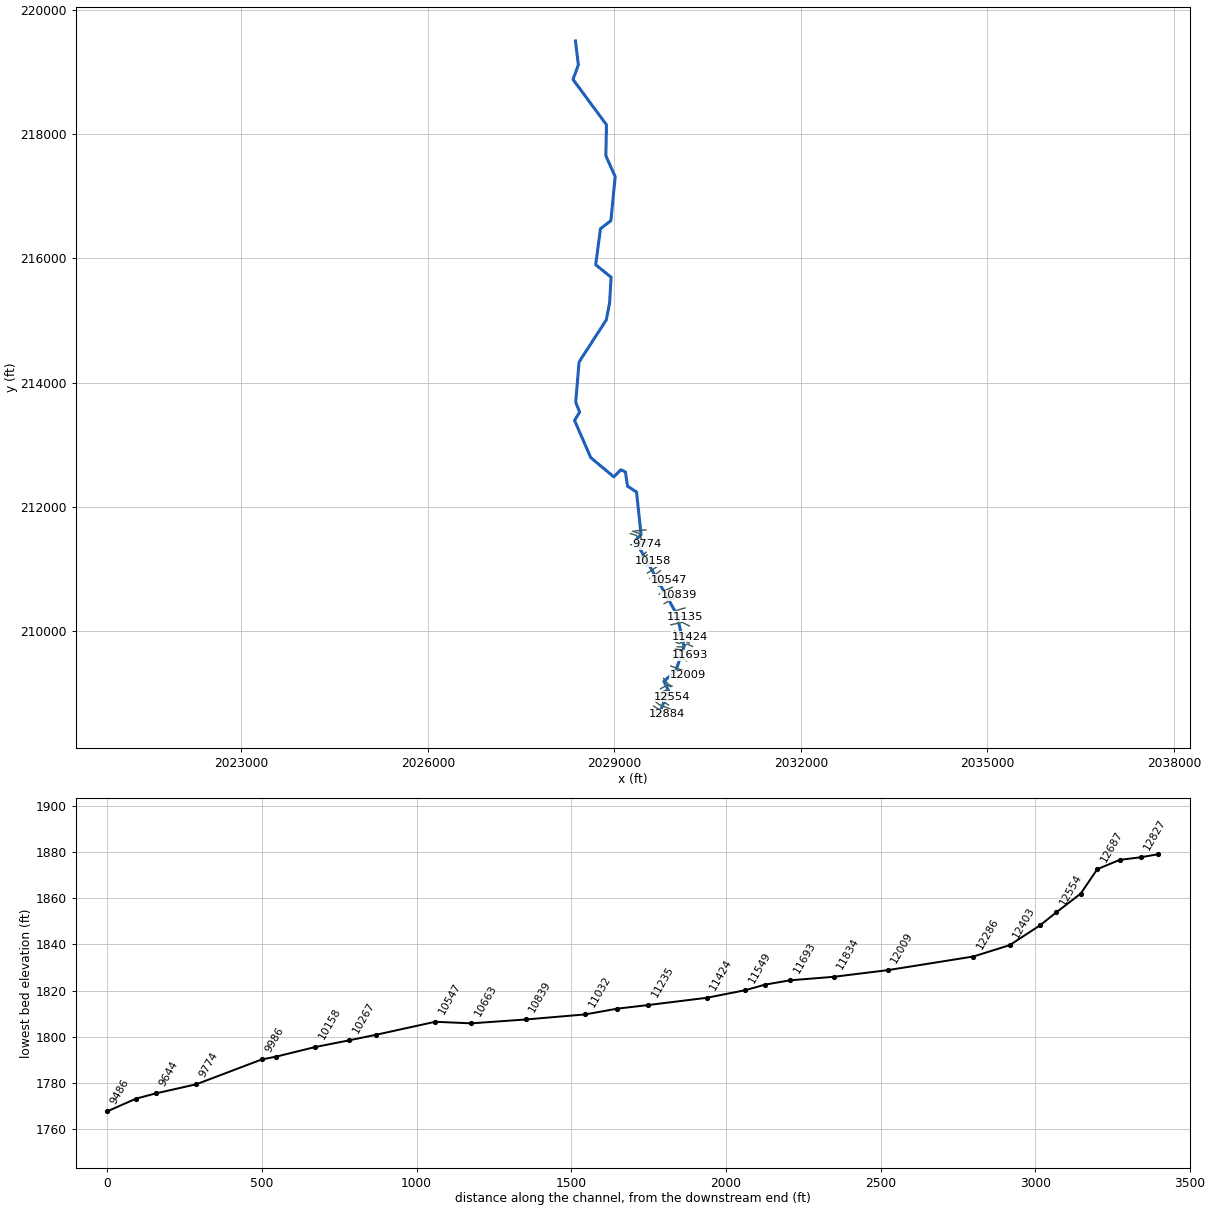
--- SPRUCERN.prj (project) ---

Proj Title=SPRUCERN
Current Plan=p01
Default Exp/Contr=0,0
English Units
Geom File=g01
Flow File=f01
Plan File=p01
BEGIN DESCRIPTION:
Stream Name: Spruce Run
Flood Zone: Approximate
Summers County, West Virginia
HEC-RAS Version: 5.0.7
Hydrology Method:
regression
Model Notes:
END DESCRIPTION:
DSS Export Rating Curves= 0
DSS Export Rating Curve Sorted= 0
DSS Export Volume Flow Curves= 0
DXF OffsetX= 0
DXF OffsetY= 0
DXF ScaleX= 0
DXF ScaleY= 0

--- SPRUCERN.p01 (plan) ---

Plan Title=Floodplain
Program Version=5.07
Short Identifier=Floodplain
Geom File=g01
Flow File=f01
Subcritical Flow
K Sum by GR= 0
Std Step Tol= 0.01
Critical Tol= 0.01
Num of Std Step Trials= 20
Max Error Tol= 0.3
Flow Tol Ratio= 0.001
Split Flow NTrial= 30
Split Flow Tol= 0.02
Split Flow Ratio= 0.02
Log Output Level= 0
Friction Slope Method= 1
Unsteady Friction Slope Method= 2
Unsteady Bridges Friction Slope Method= 1
Parabolic Critical Depth
Global Vel Dist= 0 , 0 , 0
Global Log Level= 0
CheckData=True
Encroach Param=-1 ,0,0, 0
Mapping Interval=1HOUR
Computation Time Step Use Courant=        0
Computation Time Step Use Time Series=    0
Computation Time Step Count To Double=0
Computation Time Step Max Doubling=0
Computation Time Step Max Halving=0
Computation Time Step Residence Courant=0
Run HTab= 0
Run UNet= 0
Run Sediment= 0
Run PostProcess= 0
Run WQNet= 0
Run RASMapper= 0
UNET Theta= 0
UNET Theta Warmup= 0
UNET ZTol= 0
UNET ZSATol= 0
UNET MxIter= 0
UNET Max Iter WO Improvement= 0
UNET MaxInSteps= 0
UNET DtIC= 0
UNET DtMin= 0
UNET MaxCRTS= 0
UNET WFStab= 0
UNET SFStab= 0
UNET WFX= 1
UNET SFX= 1
UNET 1D Methodology=Finite Difference
UNET DSS MLevel= 1
UNET Pardiso=0
UNET DZMax Abort= 0
UNET Use Existing IB Tables= 0
UNET Froude Reduction=False
UNET Froude Limit= 0
UNET Froude Power= 0
UNET D1 Cores= 0
UNET D2 Coriolis=0
UNET D2 Cores= 0
UNET D2 Theta= 1
UNET D2 Theta Warmup= 1
UNET D2 Z Tol= 0.01
UNET D2 Volume Tol= 0.01
UNET D2 Max Iterations= 20
UNET D2 Equation= 0
UNET D2 RampUpFraction=0.1
UNET D2 TimeSlices= 1
UNET D2 BCVolumeCheck=0
UNET D1D2 MaxIter= 0
UNET D1D2 ZTol=0.01
UNET D1D2 QTol=0.1
UNET D1D2 MinQTol=1
Write IC File= 0
Write IC File at Fixed DateTime=0
Write IC File at Sim End=0
Echo Input=False
Echo Parameters=False
Echo Output=False
Write Detailed= 0
HDF Write Warmup=0
HDF Write Time Slices=0
HDF Flush=0
HDF Face Node Velocities=0
HDF Compression= 1
HDF Chunk Size= 1
HDF Spatial Parts= 1
HDF Use Max Rows=0
HDF Fixed Rows= 1
Calibration Method= 0
Calibration Iterations= 20
Calibration Max Change=0.05
Calibration Tolerance=0.2
Calibration Maximum=1.5
Calibration Minimum=0.5
Calibration Optimization Method= 1
WQ AD Non Conservative
WQ ULTIMATE=-1
WQ Max Comp Step=1HOUR
WQ Output Interval=15MIN
WQ Output Selected Increments= 0
WQ Output face flow=0
WQ Output face velocity=0
WQ Output face area=0
WQ Output face dispersion=0
WQ Output cell volume=0
WQ Output cell surface area=0
WQ Output cell continuity=0
WQ Output cumulative cell continuity=0
WQ Output face conc=0
WQ Output face dconc_dx=0
WQ Output face courant=0
WQ Output face peclet=0
WQ Output face adv mass=0
WQ Output face disp mass=0
WQ Output cell mass=0
WQ Output cell source sink temp=0
WQ Output nsm pathways=0
WQ Output nsm derived pathways=0
WQ Output MaxMinRange=-1
WQ Daily Max Min Mean=-1
WQ Daily Range=0
WQ Daily Time=0
WQ Create Restart=0
WQ Fixed Restart=0
WQ System Summary=0
WQ Write To DSS=0
WQ Use Fixed Temperature=0
Sorting and Armoring Iterations= 10
XS Update Threshold= 0.02
Bed Roughness Predictor= 0
Hydraulics Update Threshold= 0.02
Energy Slope Method= 1
Volume Change Method= 1
Sediment Retention Method= 0
XS Weighting Method= 0
Number of US Weighted Cross Sections= 1
Number of DS Weighted Cross Sections= 1
Upstream XS Weight=0
Main XS Weight=1
Downstream XS Weight=0
Number of DS XS's Weighted with US Boundary= 1
Upstream Boundary Weight= 1
Weight of XSs Associated with US Boundary= 0
Number of US XS's Weighted with DS Boundary= 1
Downstream Boundary Weight= 0.5
Weight of XSs Associated with DS Boundary= 0.5
Percentile Method= 0
Sediment Output Level= 3
Mass or Volume Output= 0
Output Increment Type= 1
Profile and TS Output Increment= 1
XS Output Flag= 0
XS Output Increment= 10
Write Gradation File= 0
Read Gradation Hotstart= 0
Write HDF5 File= 1
Write Binary Output= 1
Write DSS Sediment File= 0
SV Curve= 0
Specific Gage Flag= 0

--- SPRUCERN.f01 (steady flow) ---

Flow Title=Flows
Program Version=5.07
Number of Profiles= 6
Profile Names=01pct,10pct,04pct,02pct,0_2pct,01plus
River Rch & RM=SPRUCERN,Main            ,12884
      69      34      47      58     101     103
River Rch & RM=SPRUCERN,Main            ,10839
     130      65      89     109     187     193
River Rch & RM=SPRUCERN,Main            ,9644
     145      73      99     121     208     214
River Rch & RM=SPRUCERN,Main            ,8444
     196      99     135     164     279     289
River Rch & RM=SPRUCERN,Main            ,7535
     375     195     261     316     528     554
River Rch & RM=SPRUCERN,Main            ,7020
     438     229     307     370     616     649
River Rch & RM=SPRUCERN,Main            ,4297
     512     269     359     433     716     757
River Rch & RM=SPRUCERN,Main            ,3213
     574     303     403     486     801     849
River Rch & RM=SPRUCERN,Main            ,3037
     638     339     449     541     890     944
Boundary for River Rch & Prof#=SPRUCERN,Main            , 1
Up Type= 0
Dn Type= 3
Dn Slope=0.066717
Boundary for River Rch & Prof#=SPRUCERN,Main            , 2
Up Type= 0
Dn Type= 3
Dn Slope=0.066717
Boundary for River Rch & Prof#=SPRUCERN,Main            , 3
Up Type= 0
Dn Type= 3
Dn Slope=0.066717
Boundary for River Rch & Prof#=SPRUCERN,Main            , 4
Up Type= 0
Dn Type= 3
Dn Slope=0.066717
Boundary for River Rch & Prof#=SPRUCERN,Main            , 5
Up Type= 0
Dn Type= 3
Dn Slope=0.066717
Boundary for River Rch & Prof#=SPRUCERN,Main            , 6
Up Type= 0
Dn Type= 3
Dn Slope=0.066717
DSS Import GetInterval= 0
DSS Import GetPeak= 0
DSS Import FillOption= 0

--- SPRUCERN.g01 (geometry) ---

Geom Title=Geometry
Program Version=5.07

River Reach=SPRUCERN        ,Main
Reach XY= 30
2029728.35893925208689.7910897712029868.59315832 209056.39177387
     2029795.759      209199.264     2029985.993      209364.942
     2030120.846      209755.4272030007.32894345210270.600681268
2029336.99835834211460.8369026742029429.11066067211557.659658059
2029356.53358614212242.4898303372029211.09765826212337.943815247
 2029177.4227558212566.653452436     2029103.181      212599.838
     2028991.375      212485.949 2028620.0942134      212795.671
     2028358.737      213394.283     2028441.375      213526.921
     2028377.486      213685.9492028431.73212715214332.995620138
     2028869.848      215010.2552028923.03207715215286.179169663
     2028946.931      215696.366     2028699.014       215897.06
     2028776.616       216477.12     2028943.479       216606.47
     2029012.727       217314.62     2028862.727      217648.647
     2028872.449      218147.953     2028334.255      218876.425
2028420.54660629219110.963809196     2028373.755      219494.859

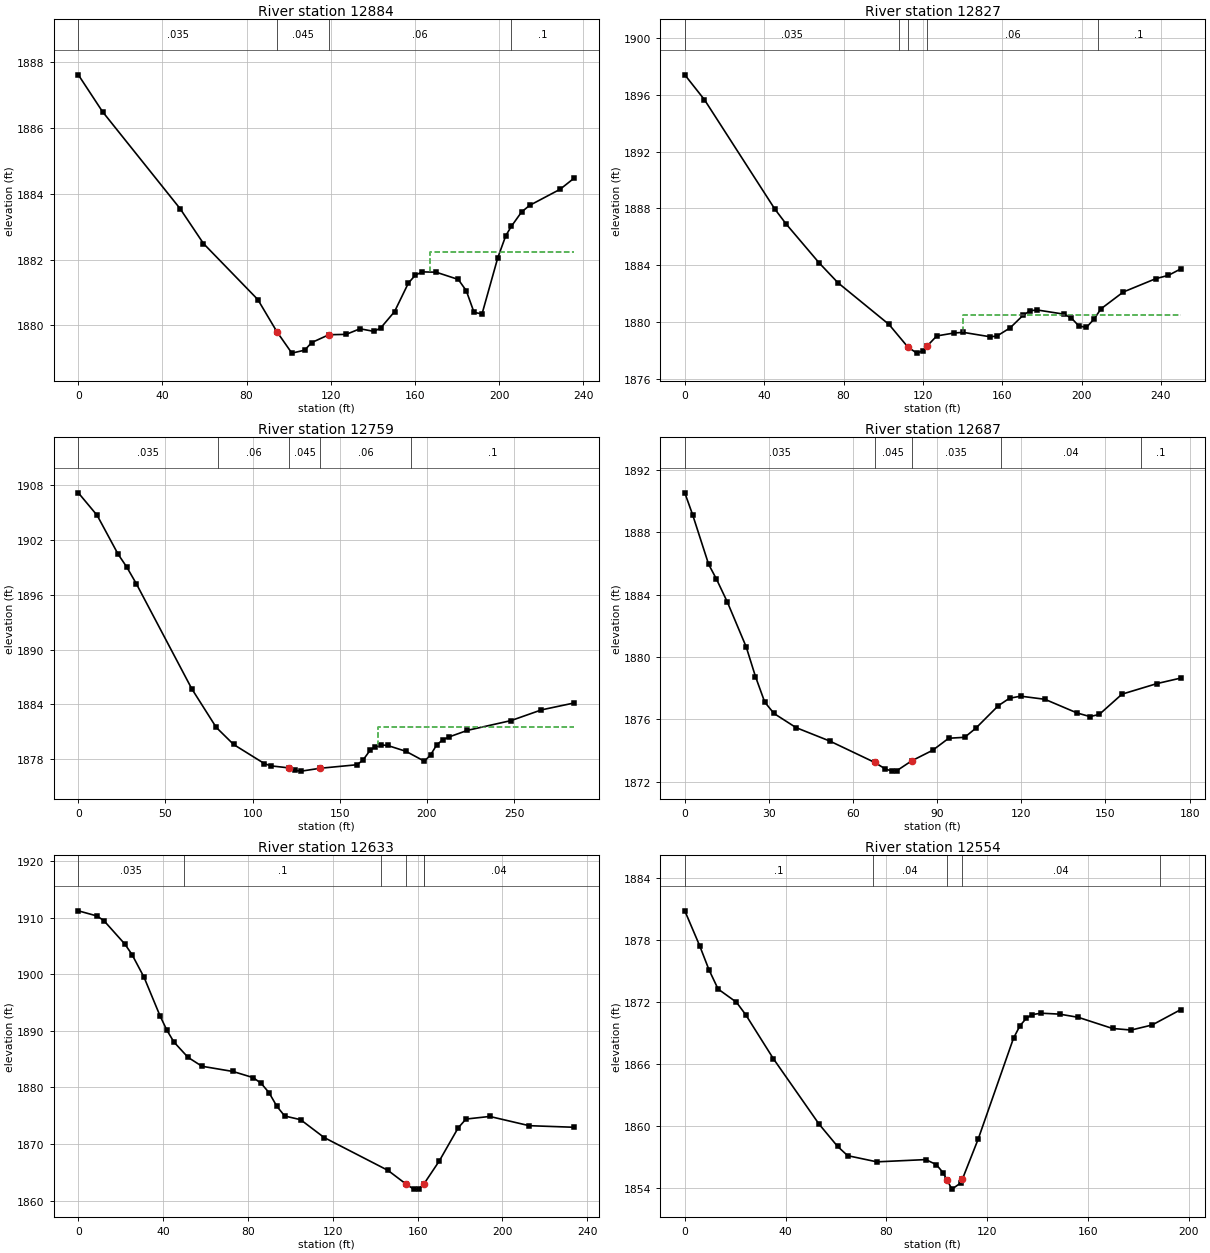
Type RM Length L Ch R = 1 ,12884   ,60.5,57.4,54.8
XS GIS Cut Line= 4
 2029627.7855992208724.0056951222029702.65364008208689.811157221
2029795.35760952208696.8592885812029848.06813695208667.315888126
#Sta/Elev= 30
       0 1887.62    11.5  1886.5    48.4 1883.55    59.5 1882.49    85.3 1880.79
    94.4 1879.81   101.5 1879.16   107.6 1879.25   110.9 1879.48   119.11879.719
   127.3 1879.73   133.9  1879.9   140.6 1879.82   143.8 1879.93   150.3 1880.42
   156.9 1881.29   160.2 1881.53   163.5 1881.63   170.1 1881.62   180.6  1881.4
   184.4 1881.06   188.1  1880.4   191.9 1880.35   199.4 1882.06   203.2 1882.73
   205.8 1883.01   210.7 1883.45   214.5 1883.65     229 1884.14   235.7 1884.48
#Mann= 4 ,-1 , 0
       0    .035       0    94.4    .045       0   119.1     .06       0
   205.8      .1       0
#XS Ineff= 2 , 0
                          167.04         1882.22
Permanent Ineff=
       F       F
Bank Sta=94.4,119.1
XS Rating Curve= 0 ,0
Exp/Cntr(USF)=0,0
Exp/Cntr=0.3,0.1

Type RM Length L Ch R = 1 ,12827   ,69.4,68,67.1
XS GIS Cut Line= 4
2029632.88409532208801.2415689012029705.95242368 208752.64933083
2029803.85678483208730.6928380722029858.20810297208701.177552725
#Sta/Elev= 30
       0  1897.4     9.9 1895.65    45.4 1887.95    51.1  1886.9    67.7 1884.17
    77.2 1882.77   102.9 1879.84   112.41878.253   116.9 1877.82   120.3    1878
   122.2 1878.33     127 1879.03   135.9 1879.24   140.4 1879.28   153.9 1878.97
   157.3 1879.02     164  1879.6   170.7 1880.51   174.1  1880.8   177.4 1880.86
   191.2 1880.56   194.9 1880.28   198.6 1879.73   202.4 1879.63   206.1 1880.19
   209.8 1880.94     221 1882.12   237.4 1883.06   243.7 1883.29   249.9 1883.74
#Mann= 5 ,-1 , 0
       0    .035       0  107.75     .06       0   112.4    .045       0
   122.2     .06       0  208.09      .1       0
#XS Ineff= 2 , 0
                             140          1880.5
Permanent Ineff=
       F       F
Bank Sta=112.4,122.2
XS Rating Curve= 0 ,0
Exp/Cntr(USF)=0,0
Exp/Cntr=0.3,0.1

Type RM Length L Ch R = 1 ,12759   ,74.8,72.2,69.9
XS GIS Cut Line= 3
2029657.09177478208875.6665842282029720.02000139208825.019133384
2029909.32868106208749.778599718
#Sta/Elev= 30
       0 1907.18    10.8 1904.71    22.8 1900.46    27.8 1899.04    33.3 1897.21
    65.1  1885.7    79.1 1881.48    89.1  1879.6   106.8  1877.5   110.4 1877.26
     121 1877.03   124.5 1876.75     128 1876.68   138.6 1876.99   159.9 1877.38
   163.3 1877.88   167.4 1878.96   170.4 1879.37   173.9 1879.55   177.5 1879.49
     188 1878.85   198.6 1877.76   202.2 1878.48   205.7 1879.58   209.2 1880.12
   212.9 1880.44   223.3 1881.15   248.3 1882.22   265.7 1883.39   284.5 1884.15
#Mann= 5 ,-1 , 0
       0    .035       0      80     .06       0     121    .045       0
   138.6     .06       0  190.78      .1       0
#XS Ineff= 2 , 0
                          171.84         1881.55
Permanent Ineff=
       F       F
Bank Sta=121,138.6
XS Rating Curve= 0 ,0
Exp/Cntr(USF)=0,0
Exp/Cntr=0.3,0.1

Type RM Length L Ch R = 1 ,12687   ,52.5,53.7,54.5
XS GIS Cut Line= 3
2029719.41680913208905.3557334562029751.62772669208899.905574006
2029869.67651801208817.177790171
#Sta/Elev= 30
       0 1890.53     2.8 1889.12     8.5 1885.94    11.3 1884.99    15.2 1883.51
    21.9 1880.64    25.2 1878.74    28.5  1877.1    31.8 1876.37    39.7 1875.46
    51.7  1874.6    67.7 1873.23    71.5 1872.81    73.9 1872.67    75.7 1872.71
    80.9 1873.33    88.4 1874.01    94.1 1874.78    99.8 1874.84   103.8 1875.43
   111.8 1876.87   115.8 1877.35   119.8 1877.48   128.4 1877.28   139.9  1876.4
   144.5 1876.17   147.8 1876.31   155.9 1877.61   168.4 1878.29   176.8 1878.64
#Mann= 5 ,-1 , 0
       0    .035       0    67.7    .045       0    80.9    .035       0
  112.67     .04       0  162.67      .1       0
Bank Sta=67.7,80.9
XS Rating Curve= 0 ,0
Exp/Cntr(USF)=0,0
Exp/Cntr=0.3,0.1

Type RM Length L Ch R = 1 ,12633   ,77.6,79.2,80.3
XS GIS Cut Line= 3
2029669.83899874208951.0865077652029742.39525077208958.342132968
2029884.39820118208882.676327276
#Sta/Elev= 30
       0 1911.18     8.8 1910.27    12.1 1909.43      22 1905.28    25.3 1903.47
      31 1899.44    38.5 1892.66    41.8 1890.07    45.1 1888.01    51.7 1885.32
    58.3 1883.74    72.9 1882.82    82.4 1881.74    86.2 1880.73    89.9 1879.09
    93.6 1876.68    97.3 1874.96   104.8 1874.31   115.9 1871.16     146 1865.36
   154.51862.949   158.1 1862.05   160.5 1862.06   162.9 1862.93   170.2 1867.02
   179.1 1872.86   182.8 1874.42     194 1874.88   212.6 1873.25   233.8 1872.97
#Mann= 6 ,-1 , 0
       0    .035       0      50      .1       0  142.92    .035       0
   154.5    .045       0   162.9    .035       0  162.92     .04       0
Bank Sta=154.5,162.9
XS Rating Curve= 0 ,0
Exp/Cntr(USF)=0,0
Exp/Cntr=0.3,0.1

Type RM Length L Ch R = 1 ,12554   ,55.1,52.3,50.1
XS GIS Cut Line= 4
2029748.74860465208976.655392598 2029806.8287624209004.849643932
2029867.26695337208983.8410697612029928.26268569208953.422832499
#Sta/Elev= 30
       0 1880.84     5.9 1877.46     9.6 1875.13    13.2 1873.27    20.5 1871.99
    24.2 1870.77    35.1 1866.54    53.3 1860.18    60.6 1858.04    64.6 1857.14
    76.2 1856.54    95.6 1856.76    99.8 1856.27   102.5 1855.48     1041854.769
     106  1853.9   109.4 1854.49   110.1 1854.85   116.4 1858.75   130.4 1868.51
     133 1869.73   135.5 1870.44   137.7 1870.79   141.4 1870.93   148.7 1870.84
   156.1 1870.53   169.7 1869.45   177.1  1869.3   185.4 1869.79   196.7 1871.27
#Mann= 5 ,-1 , 0
       0      .1       0   74.56     .04       0     104    .045       0
   110.1     .04       0  188.55     .06       0
Bank Sta=104,110.1
XS Rating Curve= 0 ,0
Exp/Cntr(USF)=0,0
Exp/Cntr=0.3,0.1

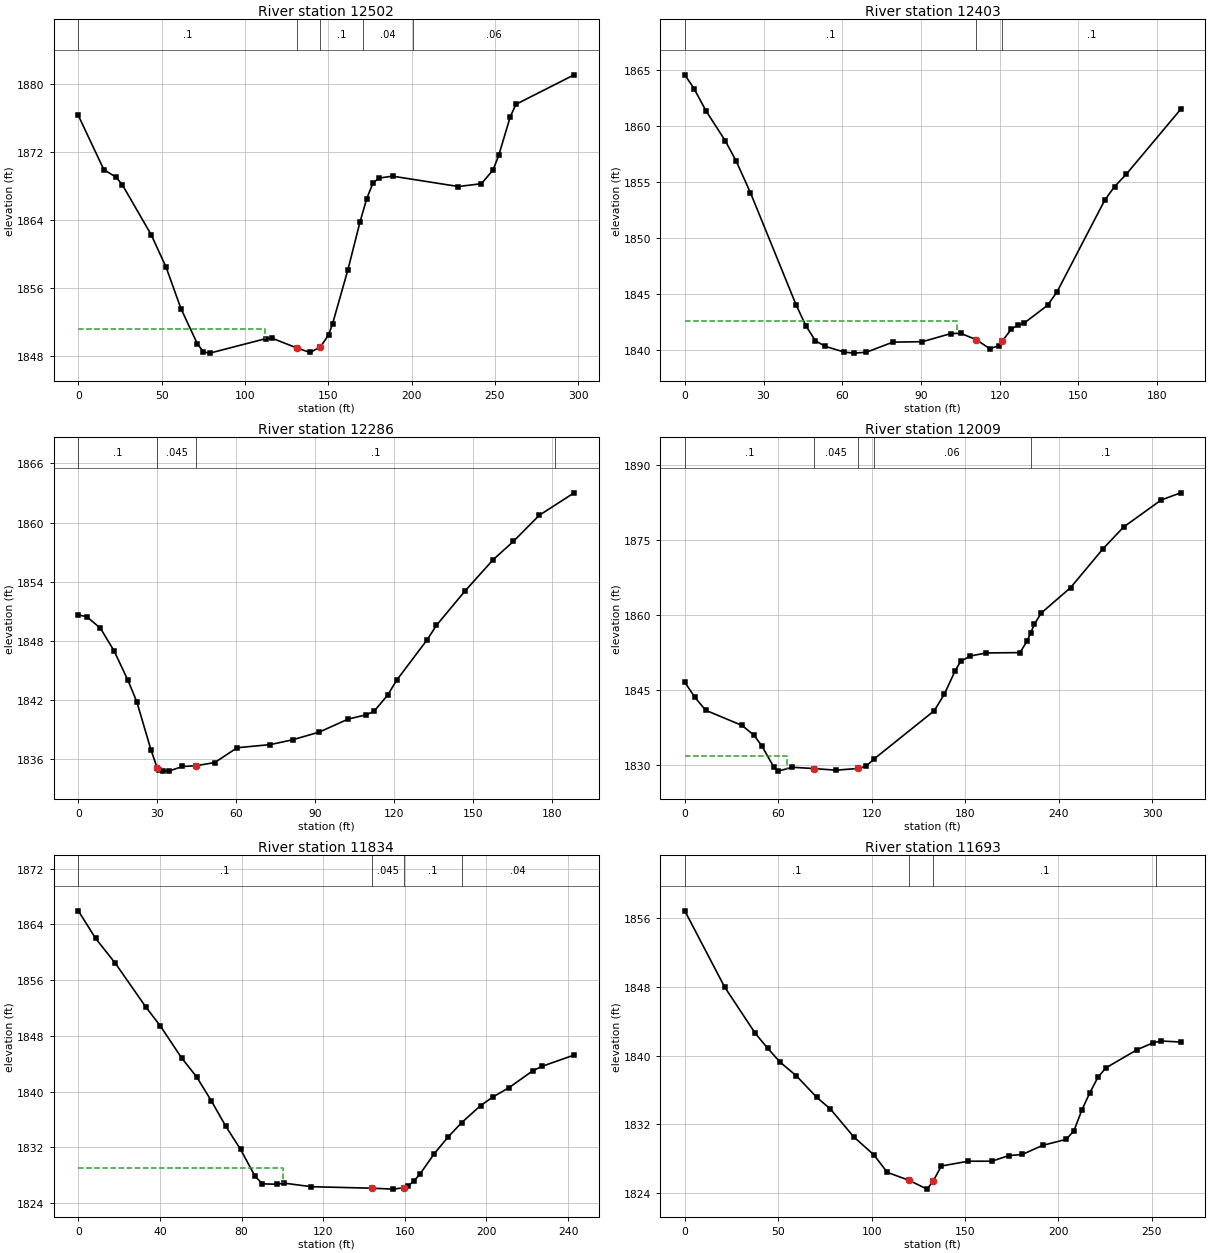
Type RM Length L Ch R = 1 ,12502   ,85.8,98.3,108.7
XS GIS Cut Line= 4
2029740.66571703209010.9933339152029829.26735127209059.429050775
2029923.66969757209005.4848528952030006.90896631209033.639311439
#Sta/Elev= 30
       0 1876.29    15.3 1869.91    22.8    1869    26.5  1868.1    43.8 1862.21
    52.7  1858.4    61.6 1853.53    71.4 1849.41    75.1 1848.42    78.9 1848.29
   112.6    1850   116.4 1850.04   131.5 1848.87   139.1 1848.37   145.3 1849.02
   150.2 1850.43   152.6 1851.75   161.8 1858.11     169  1863.7   173.1 1866.49
   176.9 1868.36   180.6 1868.92   188.6 1869.14   228.1 1867.92   241.9 1868.25
   248.9 1869.86   252.3 1871.58   259.3 1876.17   262.7 1877.61   297.6 1881.08
#Mann= 5 ,-1 , 0
       0      .1       0   131.5    .045       0   145.3      .1       0
  170.98     .04       0  200.98     .06       0
#XS Ineff= 2 , 0
          112.06 1851.08
Permanent Ineff=
       F       F
Bank Sta=131.5,145.3
XS Rating Curve= 0 ,0
Exp/Cntr(USF)=0,0
Exp/Cntr=0.3,0.1

Type RM Length L Ch R = 1 ,12403   ,131.6,117.2,95.5
XS GIS Cut Line= 4
2029740.57690801209076.8374196762029772.94144324209096.256140812
2029854.12248577209138.3300366052029908.06337781209112.438408425
#Sta/Elev= 30
       0 1864.53     3.5 1863.31     8.1 1861.31    15.4 1858.66    19.6 1856.83
      25 1854.03    42.4 1844.03    46.1 1842.17    49.8 1840.81    53.5 1840.32
    60.8  1839.8    64.5 1839.71    69.2 1839.79    79.3 1840.69    90.6 1840.73
   101.5 1841.46   105.2 1841.47     1111840.923   116.3  1840.1   119.7 1840.38
     1211840.778   124.5 1841.86     127 1842.21   129.2 1842.36   138.3 1843.98
   141.9 1845.18   160.1 1853.36   163.8 1854.56   168.3 1855.67     189 1861.45
#Mann= 3 ,-1 , 0
       0      .1       0     111    .045       0     121      .1       0
#XS Ineff= 2 , 0
          103.77 1842.54
Permanent Ineff=
       F       F
Bank Sta=111,121
XS Rating Curve= 0 ,0
Exp/Cntr(USF)=0,0
Exp/Cntr=0.3,0.1

Type RM Length L Ch R = 1 ,12286   ,265.7,277.1,285.3
XS GIS Cut Line= 3
 2029791.4661531209246.0218574162029874.09336839209144.420985278
 2029926.7299648209121.775007753
#Sta/Elev= 30
       0 1850.63     3.2 1850.45     8.4 1849.28    13.6 1846.97    18.8 1844.02
    22.2 1841.83    27.6 1836.93    29.91835.154    30.6 1834.88    32.3 1834.79
    34.6 1834.81    39.5 1835.26    44.71835.336    51.8 1835.66    60.3 1837.16
    72.9 1837.48    81.4 1837.97    91.5 1838.75   102.5 1840.07   109.3  1840.5
   112.3 1840.85   117.5 1842.51   120.9 1844.01   132.5 1848.12     136 1849.57
   146.7 1853.01   157.5 1856.22   165.2 1858.08   175.1 1860.74   188.3 1863.01
#Mann= 4 ,-1 , 0
       0      .1       0    29.9    .045       0    44.7      .1       0
  180.96     .06       0
Bank Sta=29.9,44.7
XS Rating Curve= 0 ,0
Exp/Cntr(USF)=0,0
Exp/Cntr=0.3,0.1

Type RM Length L Ch R = 1 ,12009   ,174.8,174.9,176.2
XS GIS Cut Line= 3
2029908.72722389209443.3656774512030097.83131012209376.539421414
2030183.14142421209295.494813029
#Sta/Elev= 30
       0 1846.66     6.5 1843.61    13.4 1841.04    36.7 1838.01    44.4 1836.06
    49.5 1833.88    57.2 1829.63    59.8 1828.87    69.1 1829.64      831829.378
      97 1829.06   111.2  1829.4   116.4 1829.85   121.3 1831.26   160.1 1840.95
   166.6 1844.28   173.5 1848.93     177 1850.81   183.2 1851.89   193.5  1852.5
   215.1 1852.57   219.7 1854.88     222 1856.54   224.3 1858.21   228.7 1860.47
   247.6 1865.57   268.4 1873.33   281.6 1877.68   305.7 1883.08   318.2 1884.52
#Mann= 5 ,-1 , 0
       0      .1       0      83    .045       0   111.2      .1       0
   121.3     .06       0     222      .1       0
#XS Ineff= 2 , 0
           65.72 1831.99
Permanent Ineff=
       F       F
Bank Sta=83,111.2
XS Rating Curve= 0 ,0
Exp/Cntr(USF)=0,0
Exp/Cntr=0.3,0.1

Type RM Length L Ch R = 1 ,11834   ,142.3,140.8,137.1
XS GIS Cut Line= 4
2029936.99200879209616.0528428792030026.77411123209577.433021499
2030120.90757288209557.4082762682030158.95818891209526.567583031
#Sta/Elev= 30
       0 1865.95     8.5 1861.98    18.2 1858.39      33 1852.17    40.2 1849.41
    50.6 1844.83      58 1842.09    65.2 1838.65    72.3 1834.99    79.5 1831.69
    86.6 1827.84    90.2 1826.74    97.3 1826.68   100.9 1826.84   114.1 1826.33
   143.81826.114   154.4 1825.98   159.71826.193   161.7 1826.45   164.5 1827.16
   167.3 1828.09   174.5 1831.09   181.2 1833.47   187.9 1835.54   197.1 1837.97
   203.2 1839.22   211.1 1840.56   222.8 1842.99   227.4 1843.63     243 1845.24
#Mann= 4 ,-1 , 0
       0      .1       0   143.8    .045       0   159.7      .1       0
   187.9     .04       0
#XS Ineff= 2 , 0
          100.21 1829.06
Permanent Ineff=
       F       F
Bank Sta=143.8,159.7
XS Rating Curve= 0 ,0
Exp/Cntr(USF)=0,0
Exp/Cntr=0.3,0.1

Type RM Length L Ch R = 1 ,11693   ,71.3,80.8,88.6
XS GIS Cut Line= 4
2029982.24032638209715.1408882572030072.67620696209707.330516753
2030164.75637628209664.9900817552030221.48433773209618.538924912
#Sta/Elev= 30
       0 1856.86    21.3    1848    37.7 1842.61    44.3 1840.88    50.9 1839.27
    59.7 1837.66    70.7 1835.14    77.9  1833.8    90.4 1830.56   101.2 1828.46
   108.4 1826.42     1201825.498   129.7 1824.47     1331825.421   137.3 1827.16
   151.8 1827.72   164.3 1827.72   173.4 1828.37   180.7 1828.51   191.5 1829.56
   204.1 1830.26   208.3 1831.26   212.5 1833.66   216.8 1835.69   221.1 1837.47
   225.3 1838.57   242.3 1840.72   250.8 1841.51     255 1841.71   265.4 1841.59
#Mann= 4 ,-1 , 0
       0      .1       0     120    .045       0     133      .1       0
  252.12     .04       0
Bank Sta=120,133
XS Rating Curve= 0 ,0
Exp/Cntr(USF)=0,0
Exp/Cntr=0.5,0.3

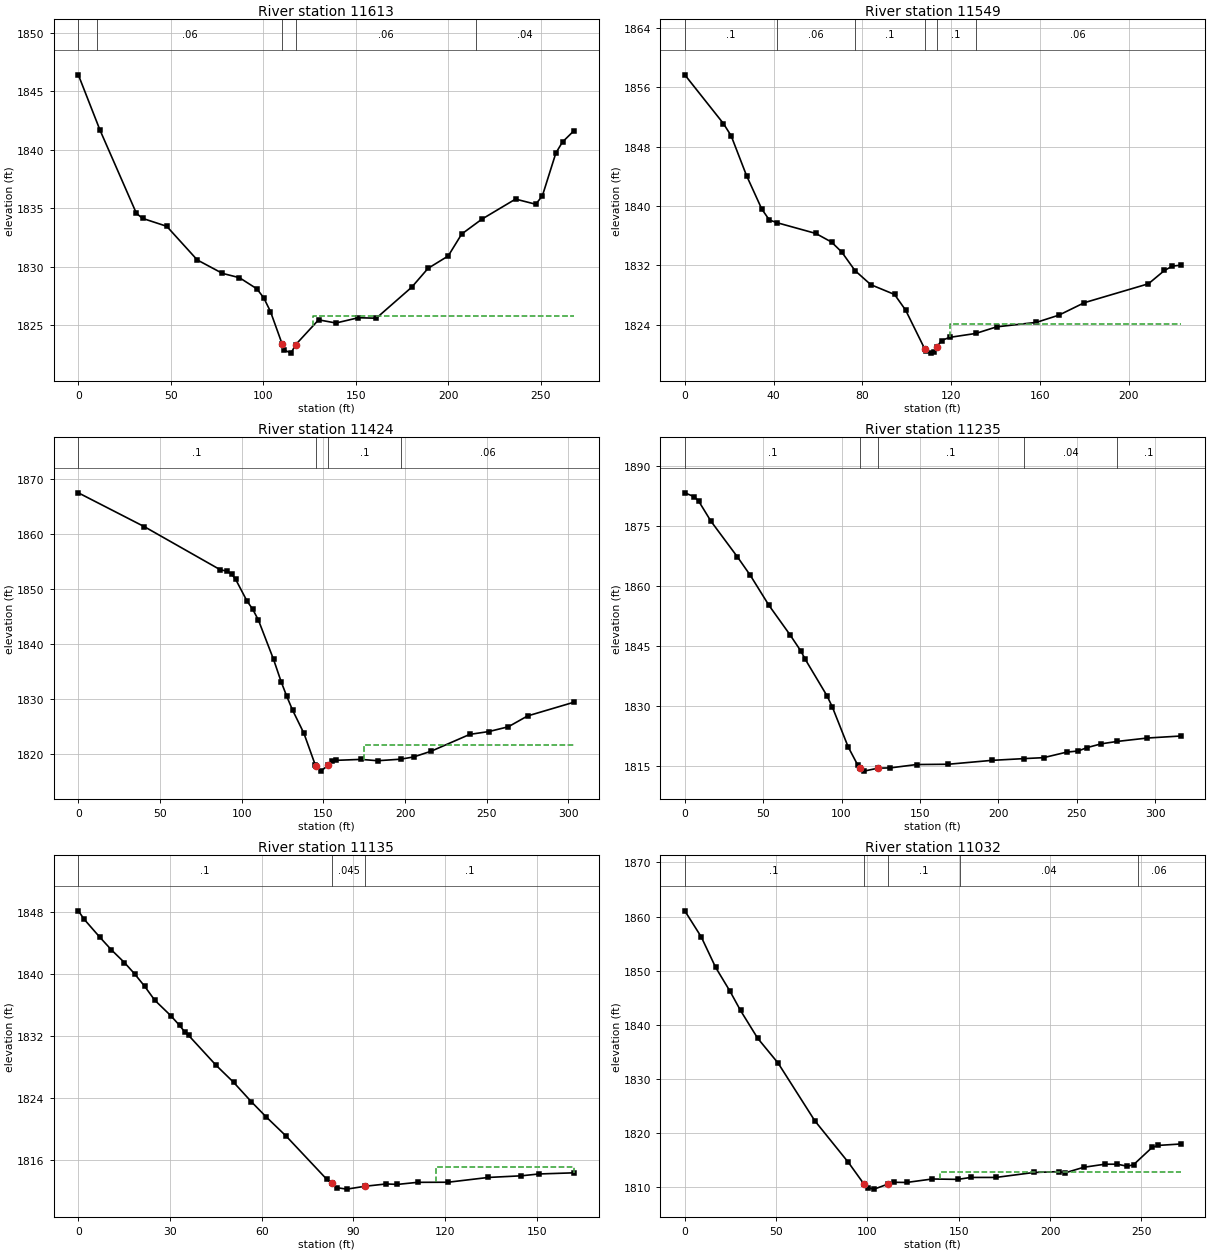
Type RM Length L Ch R = 1 ,11613   ,65,63.7,62.8
XS GIS Cut Line= 4
2030011.42645148209755.0148901492030085.41944468209750.904168305
 2030174.6221087209798.5885417012030258.48083433209758.714539809
#Sta/Elev= 30
       0 1846.42    11.7 1841.69    31.4 1834.56    34.7 1834.13    47.8 1833.45
    64.3 1830.57    77.9 1829.42    87.1 1829.05    96.5  1828.1   100.2 1827.34
   103.9 1826.15   110.2 1823.37   111.3 1822.86     115 1822.59   117.5 1823.31
   129.9 1825.44   139.3 1825.17   151.4 1825.62   161.1 1825.58   180.3 1828.24
   189.1 1829.85     200 1830.91   207.3 1832.79   218.2 1834.06   236.4 1835.78
   247.3 1835.34   250.9 1836.05   258.2 1839.72   261.8 1840.67   268.1 1841.65
#Mann= 5 ,-1 , 0
       0      .1       0      10     .06       0   110.2    .045       0
   117.5     .06       0  215.26     .04       0
#XS Ineff= 2 , 0
             101  1825.8     127          1825.8
Permanent Ineff=
       F       F
Bank Sta=110.2,117.5
XS Rating Curve= 0 ,0
Exp/Cntr(USF)=0,0
Exp/Cntr=0.5,0.3

Type RM Length L Ch R = 1 ,11549   ,125.1,125,124.6
XS GIS Cut Line= 4
2029996.67346212209823.0177189252030044.95325754209807.507015418
  2030138.246327209845.6129690282030203.64872227209815.685245748
#Sta/Elev= 30
       0 1857.66    17.4  1851.1    20.9 1849.44    27.8  1844.1    34.7 1839.57
    38.1 1838.11    41.6 1837.74      59  1836.3    66.1 1835.14    70.7  1833.8
    76.7 1831.29    83.8  1829.4    94.5 1828.08    99.5 1825.97   108.1 1820.75
   108.6 1820.43     111 1820.18   112.2 1820.34   113.5 1820.99   115.7 1821.88
   119.3  1822.3   131.1 1822.83   140.5 1823.72   158.4 1824.32   168.6  1825.3
     180 1826.97   208.9 1829.52   216.1 1831.31   219.7  1831.9   223.4 1832.02
#Mann= 6 ,-1 , 0
       0      .1       0    41.6     .06       0    76.7      .1       0
   108.1    .045       0   113.5      .1       0   131.1     .06       0
#XS Ineff= 2 , 0
             101    1824  119.59         1824.08
Permanent Ineff=
       F       F
Bank Sta=108.1,113.5
XS Rating Curve= 0 ,0
Exp/Cntr(USF)=0,0
Exp/Cntr=0.5,0.3

Type RM Length L Ch R = 1 ,11424   ,189.8,189,187.4
XS GIS Cut Line= 4
 2029970.1040394210005.5101554492030014.01622952209930.856930299
2030125.30769603209970.5260536032030207.58648583209915.953386895
#Sta/Elev= 30
       0  1867.4    40.5 1861.24    86.6 1853.48    91.2 1853.14    93.8 1852.64
    96.3 1851.69   103.2 1847.78   106.7 1846.28   110.2 1844.32   119.5 1837.16
   124.1 1833.15   127.6 1830.44   131.1 1827.98   138.1 1823.73     145 1818.02
   145.5 1817.86   148.5 1816.88   152.8 1817.93   155.5 1818.75     158 1818.84
   172.9 1819.01   183.3 1818.77   197.3 1819.05   205.2 1819.45     216  1820.5
   239.6 1823.55   251.4 1824.07   263.2 1824.93     275  1826.9   303.5  1829.4
#Mann= 4 ,-1 , 0
       0      .1       0   145.5    .045       0   152.8      .1       0
   197.3     .06       0
#XS Ineff= 2 , 0
                             175         1821.69
Permanent Ineff=
       F       F
Bank Sta=145.5,152.8
XS Rating Curve= 0 ,0
Exp/Cntr(USF)=0,0
Exp/Cntr=0.3,0.1

Type RM Length L Ch R = 1 ,11235   ,100.9,100.1,98.8
XS GIS Cut Line= 3
2029908.35447932210107.2875911542030089.70364869210148.091154262
 2030206.0693657210089.152674217
#Sta/Elev= 30
       0 1883.35     6.1 1882.36     8.9 1881.24    16.7 1876.24    33.6 1867.31
    41.8 1862.71    53.7  1855.2    67.2  1847.8    73.9 1843.87    76.9 1841.67
    90.7  1832.6    94.1 1829.81   104.2 1819.82   110.4  1815.2     1121814.514
   114.3 1813.75   123.2 1814.49   131.1 1814.56   147.9  1815.4   168.1 1815.47
   195.8 1816.44   216.3 1816.88   228.9 1817.12   243.6  1818.5     251 1818.79
   256.4 1819.61   265.7 1820.58   275.9 1821.18   295.1 1822.03   316.3 1822.53
#Mann= 5 ,-1 , 0
       0      .1       0     112    .045       0   123.2      .1       0
   216.3     .04       0   275.9      .1       0
Bank Sta=112,123.2
XS Rating Curve= 0 ,0
Exp/Cntr(USF)=0,0
Exp/Cntr=0.3,0.1

Type RM Length L Ch R = 1 ,11135   ,100.2,102.8,105.5
XS GIS Cut Line= 3
2029922.83311221210220.5998452362030083.79822516210240.758043801
 2030131.2243419 210241.07905781
#Sta/Elev= 30
       0 1848.16     1.9 1847.07       7 1844.76    10.8 1843.12    15.1 1841.46
    18.4 1840.01    21.7  1838.4      25  1836.6    30.2 1834.62    33.1 1833.35
    34.9 1832.46    36.1 1832.04    45.1 1828.17    50.8 1825.98    56.6 1823.47
    61.4 1821.53      68 1819.02    81.2 1813.47    82.91812.898    84.5 1812.36
    87.8 1812.17    93.91812.545   100.7 1812.84   104.4 1812.78     111 1813.05
   120.9 1813.06   134.1 1813.68   144.8 1813.89   150.7 1814.13   162.2 1814.28
#Mann= 3 ,-1 , 0
       0      .1       0    82.9    .045       0    93.9      .1       0
#XS Ineff= 2 , 0
                          117.15         1815.04
Permanent Ineff=
       F       F
Bank Sta=82.9,93.9
XS Rating Curve= 0 ,0
Exp/Cntr(USF)=0,0
Exp/Cntr=0.3,0.1

Type RM Length L Ch R = 1 ,11032   ,191.4,193.2,194.9
XS GIS Cut Line= 4
2029879.05776238210293.4367405272029937.30442234210310.960255668
 2030037.0720129210350.4515935962030136.55218411210378.555723668
#Sta/Elev= 30
       0 1861.06       9 1856.25    16.9 1850.61    24.8 1846.19    30.5 1842.67
    39.9 1837.54    51.1 1832.95    71.2  1822.3    89.6 1814.61    97.91810.721
   100.2 1809.93   103.7 1809.69     1111810.594   114.3 1810.96   121.4 1810.92
   135.5 1811.56   149.6 1811.49   156.6 1811.85   170.4 1811.85   191.1 1812.76
   204.8 1812.92   208.2 1812.69   218.4 1813.72     230 1814.29   236.9 1814.29
   242.3 1813.91   245.7 1814.19   255.9 1817.39   259.3 1817.76   271.5 1818.02
#Mann= 5 ,-1 , 0
       0      .1       0    97.9    .045       0     111      .1       0
  150.83     .04       0  248.12     .06       0
#XS Ineff= 2 , 0
                          139.54         1812.91
Permanent Ineff=
       F       F
Bank Sta=97.9,111
XS Rating Curve= 0 ,0
Exp/Cntr(USF)=0,0
Exp/Cntr=0.3,0.1

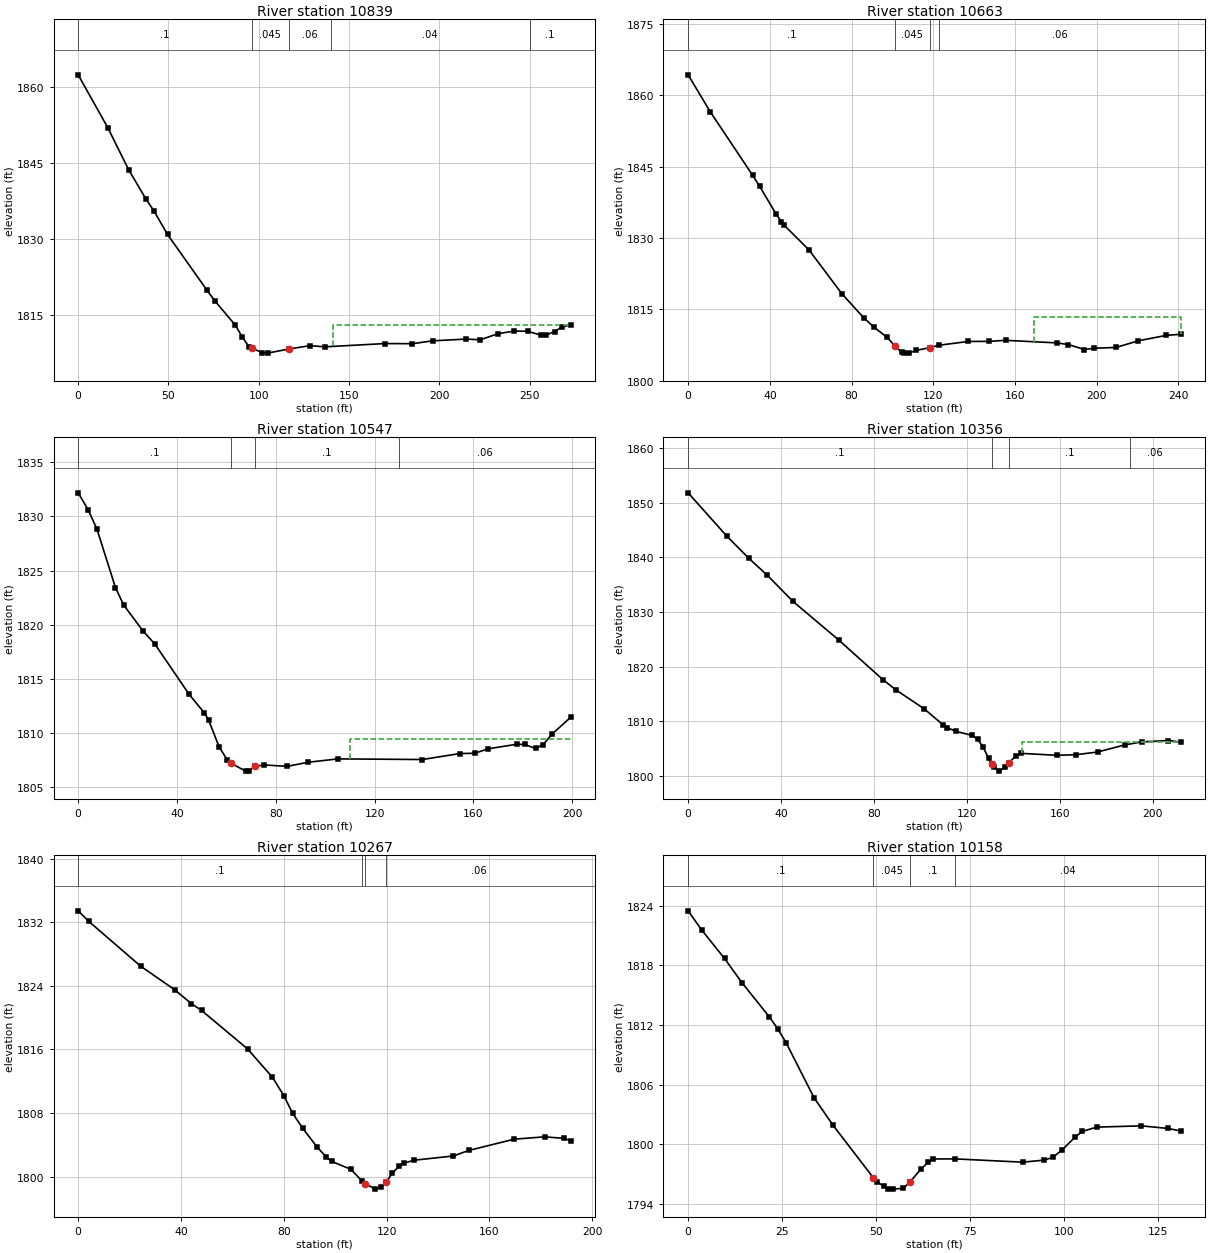
Type RM Length L Ch R = 1 ,10839   ,177.4,176.1,175.2
XS GIS Cut Line= 2
2029799.63574854210447.7986744872030037.36640723210581.903148623
#Sta/Elev= 30
       0 1862.43    16.4    1852    27.9 1843.73    37.5 1837.92    41.9  1835.6
    49.5 1830.91    71.2 1819.97    75.8 1817.76    87.1 1812.98    90.8 1810.71
    94.6 1808.75    96.1 1808.44   102.1 1807.58   104.9 1807.48   116.71808.293
   128.5 1808.96   136.6 1808.72   169.9 1809.37     185 1809.34   196.5 1809.91
   215.1 1810.26   222.7 1810.11   232.6 1811.32   241.5 1811.83     249  1811.8
   256.6    1811   259.1 1811.05   263.9 1811.73   267.9 1812.63   272.9 1813.08
#Mann= 5 ,-1 , 0
       0      .1       0    96.1    .045       0   116.7     .06       0
     140     .04       0     250      .1       0
#XS Ineff= 2 , 0
                          141.14         1813.09
Permanent Ineff=
       F       F
Bank Sta=96.1,116.7
XS Rating Curve= 0 ,0
Exp/Cntr(USF)=0,0
Exp/Cntr=0.3,0.1

Type RM Length L Ch R = 1 ,10663   ,115.4,116.1,116.8
XS GIS Cut Line= 3
2029719.03777869210597.7529801882029783.09049735210643.465914174
2029930.42101583210711.975868887
#Sta/Elev= 30
       0 1864.31    10.8 1856.57    31.6 1843.18      35 1840.88    43.1 1835.03
    45.7 1833.43    47.1 1832.67    59.2 1827.49    75.3 1818.29      86 1813.22
      91 1811.27    97.4 1809.13   101.3 1807.31   104.6 1805.95   105.8 1805.81
   108.2 1805.84   111.8  1806.4   118.2 1806.95   122.7 1807.46   137.2 1808.26
   147.3 1808.28   155.4  1808.5   180.6 1807.96   186.2 1807.61     194 1806.57
   198.7 1806.84   209.5    1807   220.4  1808.4   234.2 1809.55   241.2 1809.77
#Mann= 4 ,-1 , 0
       0      .1       0   101.3    .045       0   118.2      .1       0
   122.7     .06       0
#XS Ineff= 2 , 0
                          169.57          1813.5
Permanent Ineff=
       F       F
Bank Sta=101.3,118.2
XS Rating Curve= 0 ,0
Exp/Cntr(USF)=0,0
Exp/Cntr=0.3,0.1

Type RM Length L Ch R = 1 ,10547   ,189.4,190.4,191.4
XS GIS Cut Line= 2
2029704.79748396210729.3966220122029878.68101799210827.067373037
#Sta/Elev= 30
       0 1832.17       4 1830.62     7.6 1828.82    15.1 1823.42    18.4 1821.82
    26.4 1819.38      31 1818.23    44.9 1813.58    51.1 1811.85    52.8  1811.2
      57 1808.75    60.3 1807.54    61.8 1807.22    67.8 1806.49      69 1806.52
    71.6 1806.94    75.3 1807.06    84.6 1806.93    93.1 1807.31   105.2 1807.62
   139.3 1807.56   154.4 1808.11   160.6 1808.14   165.7 1808.54   177.5 1808.97
   180.7 1808.95   185.1 1808.58   188.2 1808.94   191.9 1809.93   199.4 1811.47
#Mann= 4 ,-1 , 0
       0      .1       0    61.8    .045       0    71.6      .1       0
     130     .06       0
#XS Ineff= 2 , 0
                             110          1809.5
Permanent Ineff=
       F       F
Bank Sta=61.8,71.6
XS Rating Curve= 0 ,0
Exp/Cntr(USF)=0,0
Exp/Cntr=0.3,0.1

Type RM Length L Ch R = 1 ,10356   ,89.3,89,88.4
XS GIS Cut Line= 2
2029570.59165137210852.330428644 2029741.2883886210978.053863993
#Sta/Elev= 30
       0 1851.81    16.6 1843.91      26 1839.88    34.1 1836.71    45.1 1831.95
    64.9 1824.84    83.8 1817.63    89.4 1815.75   101.6 1812.28   109.7 1809.35
   111.5 1808.85   115.2 1808.15   122.2 1807.43   124.6  1806.7   126.9 1805.31
   129.3 1803.21   130.61802.273   131.6 1801.68   133.9 1800.88   136.3 1801.61
   138.11802.444     141 1803.63   143.3 1804.13   158.6 1803.78   166.8 1803.88
   176.2 1804.38   187.9 1805.68   195.3 1806.23   206.7 1806.48     212 1806.19
#Mann= 4 ,-1 , 0
       0      .1       0   130.6    .045       0   138.1      .1       0
     190     .06       0
#XS Ineff= 2 , 0
                          143.46         1806.26
Permanent Ineff=
       F       F
Bank Sta=130.6,138.1
XS Rating Curve= 0 ,0
Exp/Cntr(USF)=0,0
Exp/Cntr=0.3,0.1

Type RM Length L Ch R = 1 ,10267   ,109.6,109.7,109.6
XS GIS Cut Line= 2
2029530.46634718210939.1554902632029689.92875823 211045.52065711
#Sta/Elev= 30
       0 1833.43     4.1 1832.11    24.3 1826.47    37.5 1823.51      44 1821.77
      48  1820.9    65.9 1816.06    75.6 1812.49    80.1 1810.13    83.4 1807.98
    87.4 1806.06    92.8 1803.78    96.6 1802.43    98.7  1801.9   106.1 1800.91
   110.5 1799.43   111.61799.121   115.6 1798.42   117.9 1798.65   119.91799.296
   122.3 1800.49     125 1801.31   126.8  1801.7   130.8 1802.06     146 1802.59
   151.9 1803.28   169.6  1804.7   181.5    1805   188.9 1804.81   191.7 1804.51
#Mann= 4 ,-1 , 0
       0      .1       0   110.5     .06       0   111.6    .045       0
   119.9     .06       0
Bank Sta=111.6,119.9
XS Rating Curve= 0 ,0
Exp/Cntr(USF)=0,0
Exp/Cntr=0.3,0.1

Type RM Length L Ch R = 1 ,10158   ,121.9,124.2,126.2
XS GIS Cut Line= 2
2029513.09866403211057.530101314 2029621.5973329211131.193134677
#Sta/Elev= 30
       0 1823.48     3.6 1821.56     9.7 1818.69    14.3 1816.27    21.6 1812.83
    23.8 1811.65    26.1 1810.21    33.5  1804.7    38.6 1801.91    49.31796.648
    50.3 1796.25    52.1 1795.78    53.3 1795.53    54.5 1795.51    57.3 1795.59
    59.11796.263      62 1797.54    63.9 1798.21    65.2 1798.54      71 1798.55
      89 1798.22    94.6 1798.42      97 1798.69    99.4 1799.41   102.9 1800.71
   104.9 1801.31   108.7 1801.74   120.6 1801.87   127.7 1801.61   131.1 1801.35
#Mann= 4 ,-1 , 0
       0      .1       0    49.3    .045       0    59.1      .1       0
      71     .04       0
Bank Sta=49.3,59.1
XS Rating Curve= 0 ,0
Exp/Cntr(USF)=0,0
Exp/Cntr=0.3,0.1

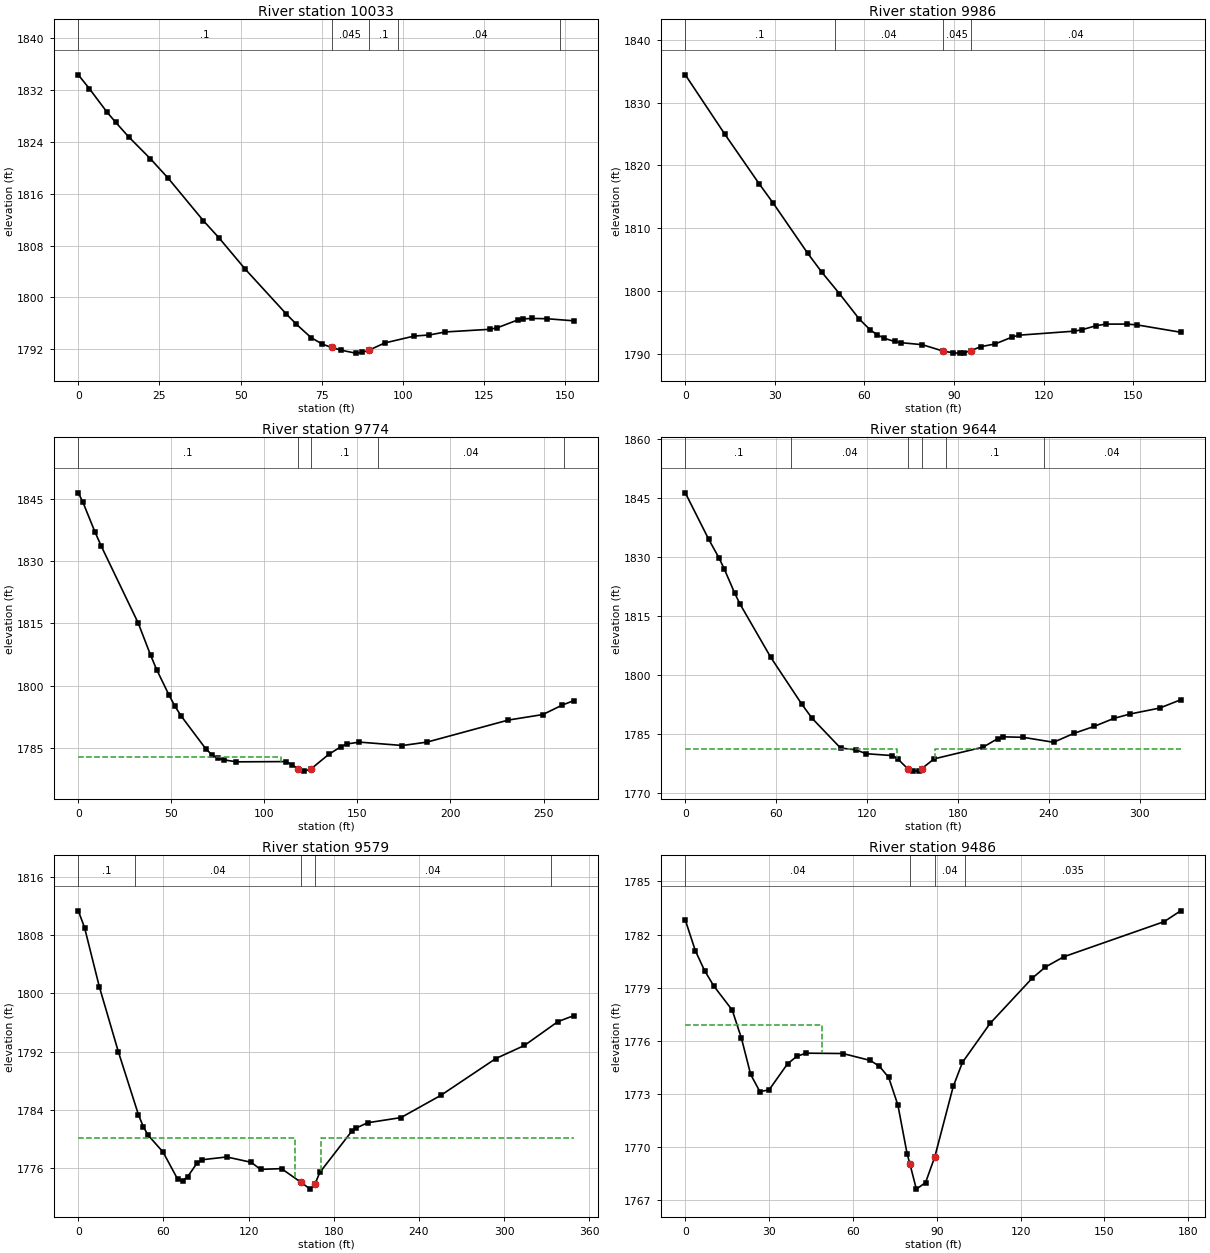
Type RM Length L Ch R = 1 ,10033   ,47.6,47.4,46.6
XS GIS Cut Line= 3
2029427.36307978211119.0982939042029449.89328579211150.371978567
2029528.74969547211232.819741145
#Sta/Elev= 30
       0 1834.38     3.4 1832.25     8.9 1828.58    11.5 1827.06    15.5 1824.81
    22.2 1821.43    27.7 1818.41    38.5 1811.87    43.3 1809.23    51.4 1804.39
    64.1 1797.44    67.2 1795.86    71.7 1793.81    75.2 1792.79    78.1 1792.28
    80.8 1791.88    85.4 1791.41    87.3 1791.52    89.4 1791.83    94.4 1792.98
   103.5 1794.05   108.1 1794.21   113.1 1794.68   126.8 1795.09   129.1 1795.33
   135.3 1796.52   136.9 1796.69   139.8 1796.77   144.4 1796.72   152.6  1796.4
#Mann= 5 ,-1 , 0
       0      .1       0    78.1    .045       0    89.4      .1       0
   98.54     .04       0  148.54     .06       0
Bank Sta=78.1,89.4
XS Rating Curve= 0 ,0
Exp/Cntr(USF)=0,0
Exp/Cntr=0.3,0.1

Type RM Length L Ch R = 1 ,9986    ,217.6,211.9,204.7
XS GIS Cut Line= 2
2029391.43715776 211157.446087682029508.34608702 211275.09494687
#Sta/Elev= 30
       0  1834.4    13.2 1824.99    24.8 1817.04    29.4 1814.03      41 1806.03
    45.7 1803.04    51.6 1799.63    58.3 1795.56    61.9 1793.87    64.2  1793.1
    66.6 1792.53    70.1 1792.01    72.3 1791.82    79.4  1791.5    86.3 1790.49
    89.8  1790.2    92.1 1790.16    93.2  1790.2    95.6 1790.55      99 1791.19
   103.7 1791.61   109.5 1792.72   111.7 1793.01   130.2 1793.65   132.8 1793.87
   137.5 1794.51   140.8 1794.77   147.8 1794.78   151.4 1794.64   165.9 1793.48
#Mann= 4 ,-1 , 0
       0      .1       0      50     .04       0    86.3    .045       0
    95.6     .04       0
Bank Sta=86.3,95.6
XS Rating Curve= 0 ,0
Exp/Cntr(USF)=0,0
Exp/Cntr=0.3,0.1

Type RM Length L Ch R = 1 ,9774    ,141.7,129.9,114.9
XS GIS Cut Line= 3
2029262.85399982211395.6157722682029402.88234073211412.870754083
2029527.23630989211399.495822683
#Sta/Elev= 30
       0 1846.51     2.4 1844.32       9 1837.02    12.3 1833.68    32.2 1815.09
    38.8  1807.4    42.1 1803.87    48.7 1797.76      52 1794.98    55.3 1792.66
    68.5 1784.76    71.8 1783.33    75.1 1782.48    78.4 1782.09      85 1781.62
   111.5 1781.68   114.8 1780.96   118.1 1779.89   121.4 1779.38     125 1779.89
   134.6 1783.43   141.2 1785.29   144.5 1785.94   151.1 1786.38   174.2 1785.56
   187.4 1786.38   231.1  1791.7   249.6 1793.02     260  1795.3   266.2 1796.37
#Mann= 5 ,-1 , 0
       0      .1       0   118.1    .045       0     125      .1       0
  161.09     .04       0  261.09     .08       0
#XS Ineff= 2 , 0
          109.13 1782.76
Permanent Ineff=
       F       F
Bank Sta=118.1,125
XS Rating Curve= 0 ,0
Exp/Cntr(USF)=0,0
Exp/Cntr=0.5,0.3

Type RM Length L Ch R = 1 ,9644    ,70.6,64.7,64.2
XS GIS Cut Line= 4
2029256.99656368211573.9713803442029355.27024009211545.013106534
2029383.66469725211455.0939786952029511.80436861211431.102419863
#Sta/Elev= 30
       0 1846.35    15.4 1834.56    22.3 1829.73    25.7 1826.99    32.5 1820.91
      36 1818.11    56.5 1804.41      77 1792.47    83.8 1788.89   102.5 1781.35
   112.7 1780.87   119.5 1779.89   136.8 1779.42   140.2  1778.6   147.1    1776
   150.5 1775.46     154 1775.54   156.1 1776.08   164.3 1778.58   196.7 1781.58
   206.3 1783.73   209.8  1784.2   223.1 1784.07   243.2 1782.81   256.5 1785.06
   269.9 1786.84   283.2 1788.92   293.7 1790.01   313.3 1791.53   327.1 1793.63
#Mann= 6 ,-1 , 0
       0      .1       0      70     .04       0   147.1    .045       0
   156.1     .04       0  172.45      .1       0  236.75     .04       0
#XS Ineff= 2 , 0
             140    1781     165            1781
Permanent Ineff=
       F       F
Bank Sta=147.1,156.1
XS Rating Curve= 0 ,0
Exp/Cntr(USF)=0,0
Exp/Cntr=0.5,0.3

Type RM Length L Ch R = 1 ,9579    ,71.2,93.3,101.6
XS GIS Cut Line= 4
 2029290.5952444211613.0174922072029412.48344733211572.641909156
2029438.54910876 211460.962312942029541.79789181211437.034754557
#Sta/Elev= 30
       0 1811.33     4.4 1809.03    14.8 1800.93    28.2 1792.02    42.4 1783.36
    45.9 1781.69    49.3 1780.54    59.7 1778.26    70.1  1774.5    73.5 1774.34
      77 1774.86    83.9  1776.8    87.3  1777.2   104.6 1777.58   121.8 1776.85
   128.4 1775.88   143.2 1775.98   157.1 1774.08   163.4 1773.17   166.8 1773.87
   170.2 1775.46   192.6 1781.08   195.5 1781.52   203.9 1782.27   227.4 1782.98
   255.5 1786.03   294.2 1791.07   314.4 1792.87     338 1796.14   349.1 1796.95
#Mann= 5 ,-1 , 0
       0      .1       0      40     .04       0   157.1    .045       0
   166.8     .04       0  333.08     .08       0
#XS Ineff= 2 , 0
             153  1780.2     171          1780.2
Permanent Ineff=
       F       F
Bank Sta=157.1,166.8
XS Rating Curve= 0 ,0
Exp/Cntr(USF)=0,0
Exp/Cntr=0.5,0.3

Type RM Length L Ch R = 1 ,9486    ,86.9,86.3,85.6
XS GIS Cut Line= 2
2029330.51963274 211617.231526752029507.05463773211633.923445584
#Sta/Elev= 30
       0 1782.82     3.6 1781.09     6.9 1779.97    10.2  1779.1    16.8 1777.74
    20.1 1776.15    23.4 1774.11    26.7 1773.14      30 1773.24    36.6 1774.71
    39.9 1775.13    43.2 1775.31    56.4 1775.29    66.2  1774.9    69.5 1774.57
    72.8 1773.94    76.1 1772.38    79.4 1769.63    80.4 1769.06    82.7 1767.64
      86 1768.01    89.3 1769.46    95.9 1773.43    99.2 1774.79   109.1 1776.99
   124.1 1779.53   128.9 1780.17   135.5 1780.75   171.4 1782.73   177.3 1783.34
#Mann= 4 ,-1 , 0
       0     .04       0    80.4    .045       0    89.3     .04       0
     100    .035       0
#XS Ineff= 2 , 0
           48.95 1776.88
Permanent Ineff=
       F       F
Bank Sta=80.4,89.3
XS Rating Curve= 0 ,0
Exp/Cntr(USF)=0,0
Exp/Cntr=0.3,0.1