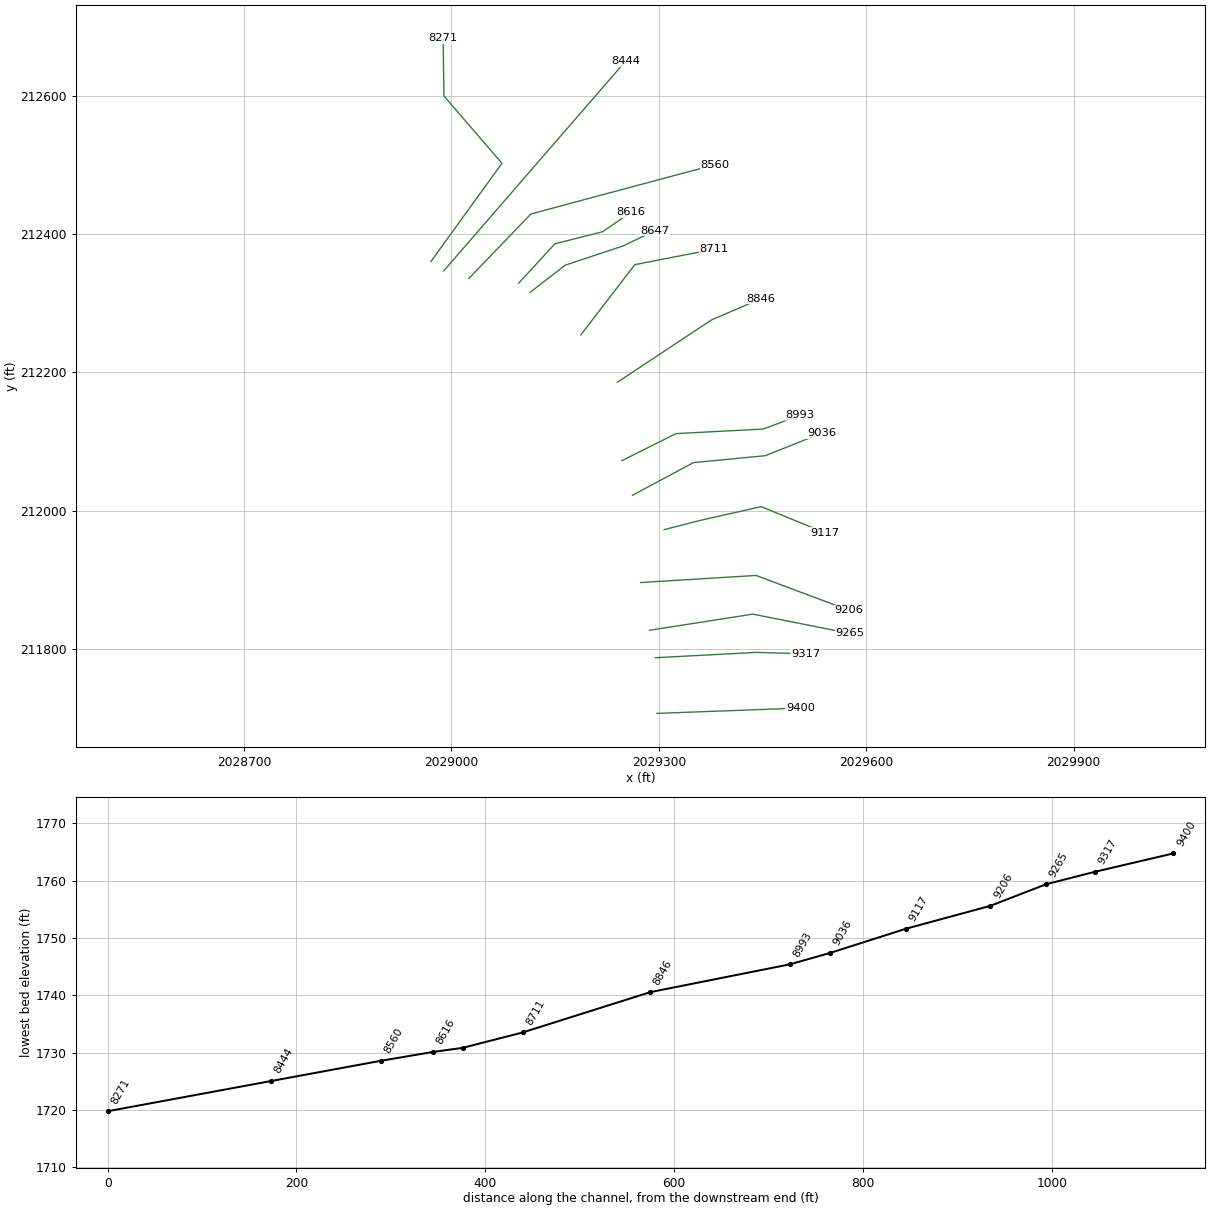
HEC-RAS study SPRUCERN.prj: SPRUCERN

--- SPRUCERN.g01 (geometry) --- (continued)

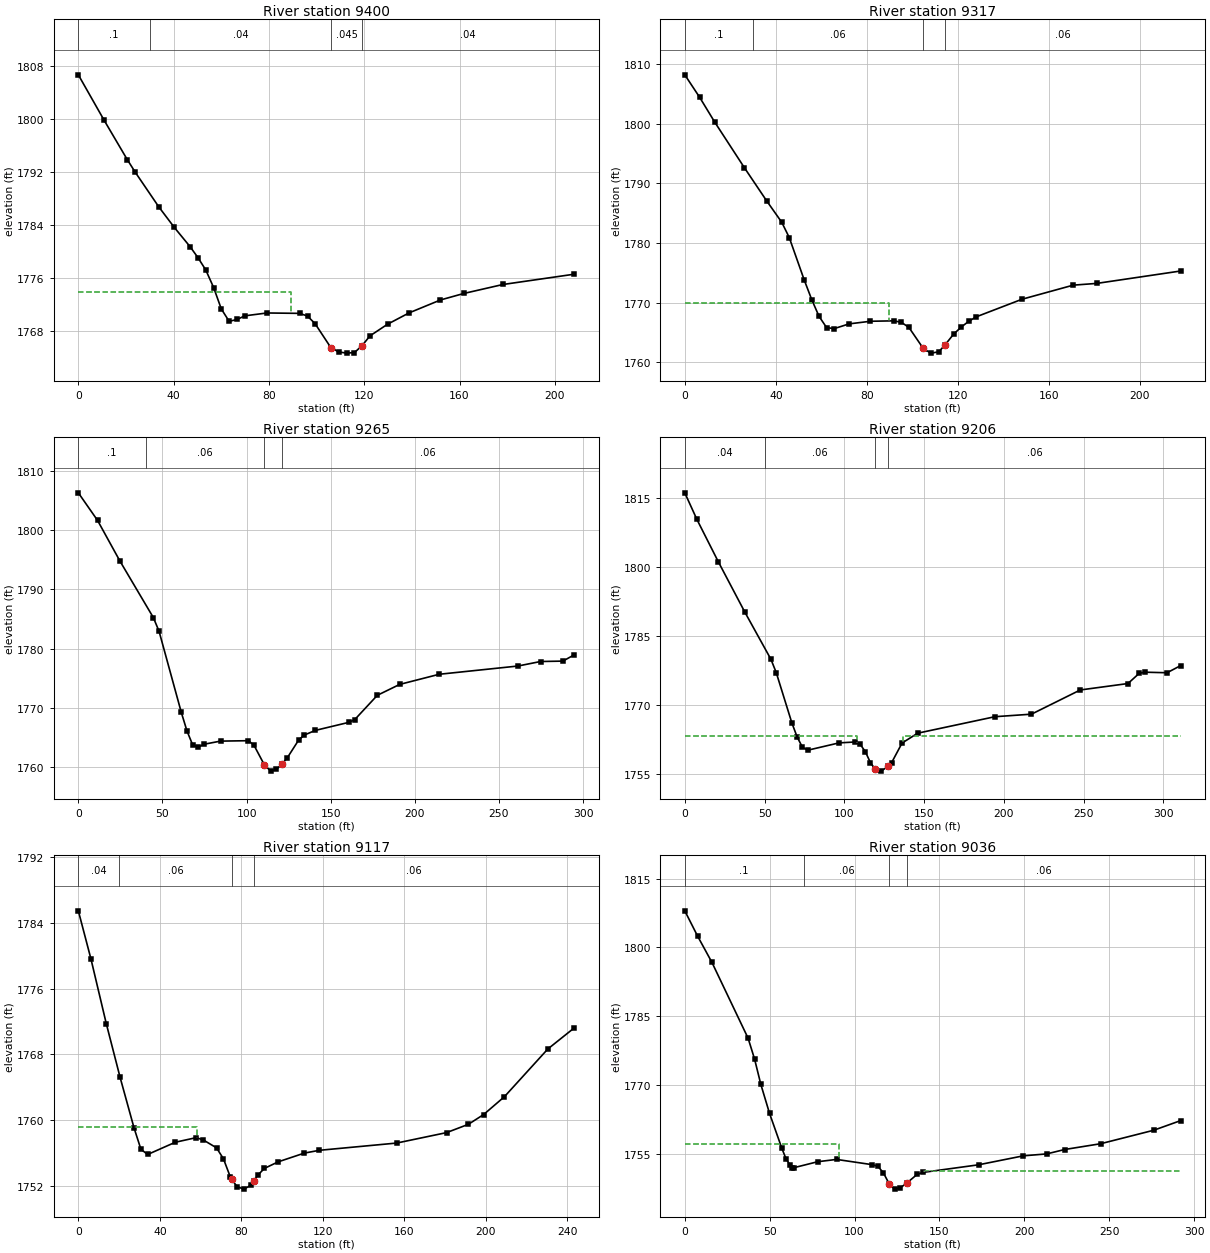
Type RM Length L Ch R = 1 ,9400    ,82.7,83,83
XS GIS Cut Line= 2
2029297.10118925211706.7709720142029505.02408074211714.451500988
#Sta/Elev= 30
       0 1806.67    10.8 1799.84    20.6 1793.86    23.9 1791.99    33.8 1786.76
    40.3 1783.67    46.9 1780.78    50.2 1779.13    53.5 1777.26    56.8 1774.61
      60  1771.4    63.3 1769.53    66.6 1769.81    69.9 1770.36    79.2 1770.79
    92.9 1770.73    96.2 1770.32    99.4 1769.16     106 1765.56   109.3 1764.92
   112.6 1764.74   115.9 1764.83   119.1 1765.87   122.4 1767.34   129.8  1769.1
   138.8  1770.8     152 1772.75   161.8 1773.73   178.2 1775.08   208.1 1776.63
#Mann= 4 ,-1 , 0
       0      .1       0      30     .04       0     106    .045       0
   119.1     .04       0
#XS Ineff= 2 , 0
           89.14 1773.98
Permanent Ineff=
       F       F
Bank Sta=106,119.1
XS Rating Curve= 0 ,0
Exp/Cntr(USF)=0,0
Exp/Cntr=0.3,0.1

Type RM Length L Ch R = 1 ,9317    ,50.9,51.9,53
XS GIS Cut Line= 3
2029294.86412538211787.2845579172029440.48562769211794.974679376
2029512.48849942211792.977730234
#Sta/Elev= 30
       0 1808.17     6.5 1804.42    13.1 1800.28    26.2  1792.6      36 1787.04
    42.6 1783.47    45.9 1780.91    52.5 1773.78    55.8 1770.49      59  1767.7
    62.3 1765.83    65.6 1765.64    72.2 1766.44    81.6 1766.88    91.9 1766.95
    95.2  1766.7    98.5 1765.84   104.6 1762.44     105 1762.22   108.3 1761.54
   111.6 1761.76   114.41762.939   118.2 1764.75   121.5 1765.91   124.7 1766.85
     128 1767.61   148.2 1770.57   170.7 1772.93     181 1773.22   217.9  1775.3
#Mann= 4 ,-1 , 0
       0      .1       0      30     .06       0   104.6    .045       0
   114.4     .06       0
#XS Ineff= 2 , 0
           89.93 1769.94
Permanent Ineff=
       F       F
Bank Sta=104.6,114.4
XS Rating Curve= 0 ,0
Exp/Cntr(USF)=0,0
Exp/Cntr=0.5,0.3

Type RM Length L Ch R = 1 ,9265    ,59.8,58.9,58
XS GIS Cut Line= 3
2029286.74987584211827.0426286852029436.00845145211850.364281125
2029576.87123218211822.378298198
#Sta/Elev= 30
       0 1806.28    11.4 1801.64    24.7 1794.79    44.6 1785.24      48 1782.92
    61.2 1769.26    64.6 1766.11    67.9 1763.82    71.2 1763.37    74.5 1763.88
    84.5 1764.42   101.1 1764.49   104.4 1763.72   110.6  1760.4   114.4 1759.36
   117.7 1759.65     121 1760.52   124.3 1761.65     131 1764.62   134.3 1765.44
   140.9 1766.23   160.9 1767.59   164.3 1768.05   177.7 1772.14     191 1773.98
   214.5 1775.69   261.3 1777.08   274.7 1777.84     288 1777.91   294.7 1778.96
#Mann= 4 ,-1 , 0
       0      .1       0      40     .06       0   110.6    .045       0
     121     .06       0
#XS Ineff= 2 , 0
              95  1764.3     136          1764.3
Permanent Ineff=
       F       F
Bank Sta=110.6,121
XS Rating Curve= 0 ,0
Exp/Cntr(USF)=0,0
Exp/Cntr=0.5,0.3

Type RM Length L Ch R = 1 ,9206    ,87.5,89.1,90.7
XS GIS Cut Line= 3
2029273.68975047211896.0747199062029440.67278194211906.336246979
2029575.00549999 211855.96147771
#Sta/Elev= 30
       0 1816.19     7.6 1810.39    21.1 1801.12    37.6 1790.24      54 1779.94
    57.3 1777.07    67.1 1766.11    70.4 1763.05    73.7 1760.82      77 1760.15
    96.7 1761.75   106.6 1761.94   109.9 1761.46   113.2 1759.82   116.4 1757.41
   119.1 1756.16   119.7 1755.84     123  1755.6   127.5 1756.63   129.6 1757.42
   136.2 1761.72     146 1763.86   194.4 1767.45   217.3    1768   247.9 1773.27
   277.8 1774.67   284.8 1776.88   288.3 1777.14   302.3 1777.02   310.8 1778.57
#Mann= 4 ,-1 , 0
       0     .04       0      50     .06       0   119.1    .045       0
   127.5     .06       0
#XS Ineff= 2 , 0
             108  1763.2     137          1763.2
Permanent Ineff=
       F       F
Bank Sta=119.1,127.5
XS Rating Curve= 0 ,0
Exp/Cntr(USF)=0,0
Exp/Cntr=0.5,0.3

Type RM Length L Ch R = 1 ,9117    ,82.4,81.1,79.8
XS GIS Cut Line= 4
2029307.72541229211972.594010267 2029358.9281583211985.733362366
2029448.32022737212005.8825131882029539.67987212211968.254518263
#Sta/Elev= 30
       0 1785.45     6.2 1779.59    13.7 1771.75    20.5  1765.2    27.3 1759.09
    30.7 1756.47      34 1755.83    47.6 1757.32    57.7 1757.87    61.1 1757.63
    67.8 1756.64    71.2 1755.31    74.5 1753.15    75.2 1752.85    77.9 1751.91
    81.3 1751.62    84.6 1752.09    86.2 1752.64      88  1753.3    91.3 1754.14
    98.1 1754.94   110.9    1756   118.3 1756.34   156.2 1757.22   180.7 1758.49
   191.4  1759.5   198.9 1760.69   209.1 1762.86   230.4 1768.66   243.3 1771.21
#Mann= 4 ,-1 , 0
       0     .04       0      20     .06       0    75.2    .045       0
    86.2     .06       0
#XS Ineff= 2 , 0
           58.28 1759.21
Permanent Ineff=
       F       F
Bank Sta=75.2,86.2
XS Rating Curve= 0 ,0
Exp/Cntr(USF)=0,0
Exp/Cntr=0.5,0.3

Type RM Length L Ch R = 1 ,9036    ,42.8,42.3,41.9
XS GIS Cut Line= 4
2029261.84025236212022.2894042332029350.18477047212069.587814055
2029453.99984955212079.5795353242029535.41850615212111.979133296
#Sta/Elev= 30
       0 1807.97     7.6 1802.42      16 1796.73    37.3 1780.22    41.1 1775.69
    44.8 1770.16    49.9 1763.88    57.2 1756.22    59.7  1753.9      62 1752.63
    63.4 1752.07    64.4 1752.04    78.3 1753.33    89.4 1753.83   110.5 1752.68
   113.8 1752.32     117  1750.9   120.51748.452   123.6 1747.36   126.9 1747.63
   130.71748.657   136.8 1750.55   140.1 1750.99   173.1 1752.66   199.4 1754.61
   213.2 1755.03   223.8 1755.99     245 1757.25   276.3 1760.19   292.1 1762.28
#Mann= 4 ,-1 , 0
       0      .1       0      70     .06       0   120.5    .045       0
   130.7     .06       0
#XS Ineff= 2 , 0
           90.82 1757.09     141          1751.4
Permanent Ineff=
       F       F
Bank Sta=120.5,130.7
XS Rating Curve= 0 ,0
Exp/Cntr(USF)=0,0
Exp/Cntr=0.5,0.3

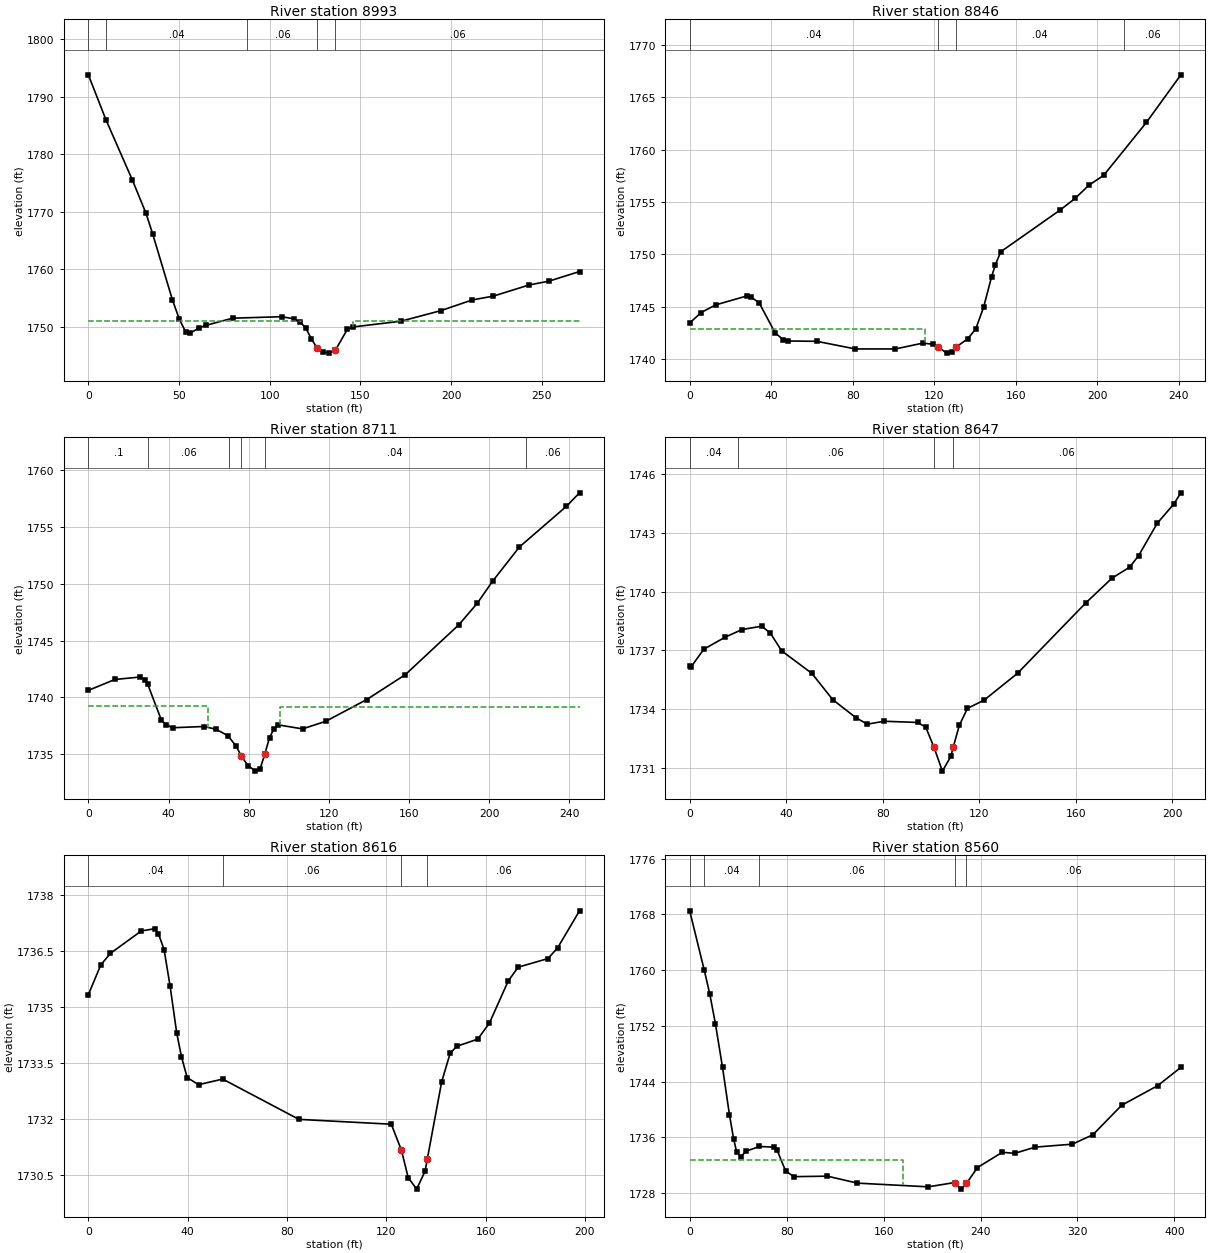
Type RM Length L Ch R = 1 ,8993    ,142.7,147.8,152.5
XS GIS Cut Line= 4
2029246.63663364212072.3864123482029324.99738584212111.566788446
2029450.93430901212118.0968511292029504.35552846 212138.07933915
#Sta/Elev= 30
       0 1793.82     9.7    1786    24.3 1775.49    31.8 1769.71    35.5  1766.1
    46.3 1754.71    50.1 1751.35    53.8 1748.98    56.1 1748.86      61 1749.77
    64.8 1750.22    79.5 1751.47   106.6 1751.73   113.2 1751.36   116.5 1750.89
   119.8  1749.8     123 1747.86   126.3  1746.2   129.6 1745.59   132.9 1745.39
   136.2  1745.9   142.8 1749.53     146 1749.95   172.3 1750.94   194.2 1752.77
   211.7 1754.65   223.3 1755.31   243.1 1757.26   253.9 1757.91   270.8 1759.59
#Mann= 5 ,-1 , 0
       0      .1       0      10     .04       0   87.61     .06       0
   126.3    .045       0   136.2     .06       0
#XS Ineff= 2 , 0
             117  1750.9     146          1750.9
Permanent Ineff=
       F       F
Bank Sta=126.3,136.2
XS Rating Curve= 0 ,0
Exp/Cntr(USF)=0,0
Exp/Cntr=0.5,0.3

Type RM Length L Ch R = 1 ,8846    ,131.4,135.1,136.5
XS GIS Cut Line= 3
2029240.09010128 212185.834560542029376.11682123212275.952637122
2029447.72335542212306.779856925
#Sta/Elev= 30
       0 1743.42     5.6 1744.42    12.7 1745.15    27.9    1746    30.2 1745.89
    34.1 1745.35      42 1742.46    45.9 1741.84    48.2  1741.7    62.4 1741.67
    81.3 1740.94     101 1740.94   114.5  1741.5   119.2 1741.39     1221741.101
   126.3 1740.54   128.6 1740.64   130.6 1741.09   136.4  1741.9   140.4 1742.84
   144.3 1744.95   148.2 1747.85     150 1748.97   152.7 1750.24   181.8 1754.22
   189.2 1755.34     196 1756.61   203.2 1757.54   224.2 1762.61   241.1 1767.16
#Mann= 4 ,-1 , 0
       0     .04       0     122    .045       0   130.6     .04       0
  213.17     .06       0
#XS Ineff= 2 , 0
          115.51 1742.89
Permanent Ineff=
       F       F
Bank Sta=122,130.6
XS Rating Curve= 0 ,0
Exp/Cntr(USF)=0,0
Exp/Cntr=0.3,0.1

Type RM Length L Ch R = 1 ,8711    ,68.9,63.4,57.2
XS GIS Cut Line= 3
2029187.13722725212254.3334380122029265.29395559212355.977706011
2029380.03648559212378.366492352
#Sta/Elev= 30
       0 1740.62    13.2 1741.58    25.9  1741.8    28.2 1741.55    29.6 1741.17
    36.5 1737.98    38.9  1737.6      42 1737.33    57.6 1737.44    63.5 1737.21
    69.6 1736.64    73.8  1735.7    76.3 1734.84    79.7 1733.99    83.4 1733.51
    85.7 1733.71      88 1734.98    90.4 1736.46    92.7 1737.26    94.5 1737.59
   106.9 1737.23   118.5  1737.9   138.9 1739.81   158.2 1742.01     185 1746.42
   194.1  1748.3   201.7 1750.23   215.1 1753.25   238.5 1756.82   245.1 1758.02
#Mann= 6 ,-1 , 0
       0      .1       0      30     .06       0      70     .04       0
    76.3    .045       0      88     .04       0  218.22     .06       0
#XS Ineff= 2 , 0
           59.86 1739.21   95.73         1739.15
Permanent Ineff=
       F       F
Bank Sta=76.3,88
XS Rating Curve= 0 ,0
Exp/Cntr(USF)=0,0
Exp/Cntr=0.5,0.3

Type RM Length L Ch R = 1 ,8647    ,31.8,31.5,31.3
XS GIS Cut Line= 4
2029113.72372475  212315.79222362029164.31300643 212355.09769752
2029249.15204852212383.3489771372029294.14623491212405.226688363
#Sta/Elev= 30
       0 1736.19      .6 1736.16     5.8 1737.06    14.7 1737.68    21.7 1738.07
    29.8 1738.24    33.4 1737.89    38.1 1736.98    50.6 1735.83    59.3 1734.48
    68.9 1733.56    73.6 1733.23    80.5 1733.38    94.4 1733.32    97.8 1733.08
   101.21732.054   104.7 1730.83   108.2 1731.58   109.21732.057   111.7 1733.17
   115.1 1734.04     122 1734.46   135.9 1735.84   164.1 1739.43     175  1740.7
   182.3 1741.26     186 1741.85   193.7  1743.5   200.6 1744.49   203.5 1745.06
#Mann= 4 ,-1 , 0
       0     .04       0      20     .06       0   101.2    .045       0
   109.2     .06       0
#XS Ineff= 2 , 0
              96    1733     114            1733
Permanent Ineff=
       F       F
Bank Sta=101.2,109.2
XS Rating Curve= 0 ,0
Exp/Cntr(USF)=0,0
Exp/Cntr=0.5,0.3

Type RM Length L Ch R = 1 ,8616    ,55.3,55.6,55.2
XS GIS Cut Line= 4
2029097.36314395212329.2614972672029149.71112736212386.171059579
2029218.66436768  212403.60610572029259.34133466212431.542785865
#Sta/Elev= 30
       0 1735.32       5 1736.12     8.9 1736.43    21.3 1737.03    26.7 1737.09
    28.2 1736.96    30.5 1736.53    32.9 1735.56    35.6 1734.29    37.5 1733.66
    39.8  1733.1    44.4 1732.91    54.1 1733.06    84.8 1731.98     122 1731.85
   126.1 1731.15   128.8 1730.42   132.2 1730.11   135.6 1730.59   136.51730.916
   142.3 1732.99   145.7 1733.75   148.4 1733.94   156.8 1734.13   161.5 1734.56
   169.1 1735.69   173.1 1736.06   185.1 1736.29     189 1736.58   197.8 1737.57
#Mann= 4 ,-1 , 0
       0     .04       0    54.1     .06       0   126.1    .045       0
   136.5     .06       0
#XS Ineff= 2 , 0
             121  1731.8     141          1731.8
Permanent Ineff=
       F       F
Bank Sta=126.1,136.5
XS Rating Curve= 0 ,0
Exp/Cntr(USF)=0,0
Exp/Cntr=0.5,0.3

Type RM Length L Ch R = 1 ,8560    ,107.1,116.5,124.7
XS GIS Cut Line= 4
2029025.15157986212335.9489965832029114.87742091212429.226764485
2029229.21408124212459.9965764032029381.34211199212500.668297581
#Sta/Elev= 30
       0  1768.5    11.9 1760.07    16.5 1756.63    21.2 1752.32    27.1 1746.03
    32.8 1739.25    36.2 1735.81    38.7 1733.93    42.1  1733.2    46.7 1734.02
    57.6 1734.68    69.9 1734.58    72.2 1734.12    79.2 1731.15    86.1 1730.35
   113.6 1730.42   138.4 1729.42   196.8 1728.89   218.61729.503     224 1728.56
   228.41729.373   237.4 1731.65     258 1733.85   268.1 1733.69   285.1 1734.59
   315.7 1735.01   332.7 1736.36   356.4 1740.59   386.2 1743.41   405.3 1746.03
#Mann= 5 ,-1 , 0
       0      .1       0    11.9     .04       0    57.6     .06       0
   218.6    .045       0   228.4     .06       0
#XS Ineff= 2 , 0
          175.63  1732.8
Permanent Ineff=
       F       F
Bank Sta=218.6,228.4
XS Rating Curve= 0 ,0
Exp/Cntr(USF)=0,0
Exp/Cntr=0.3,0.1

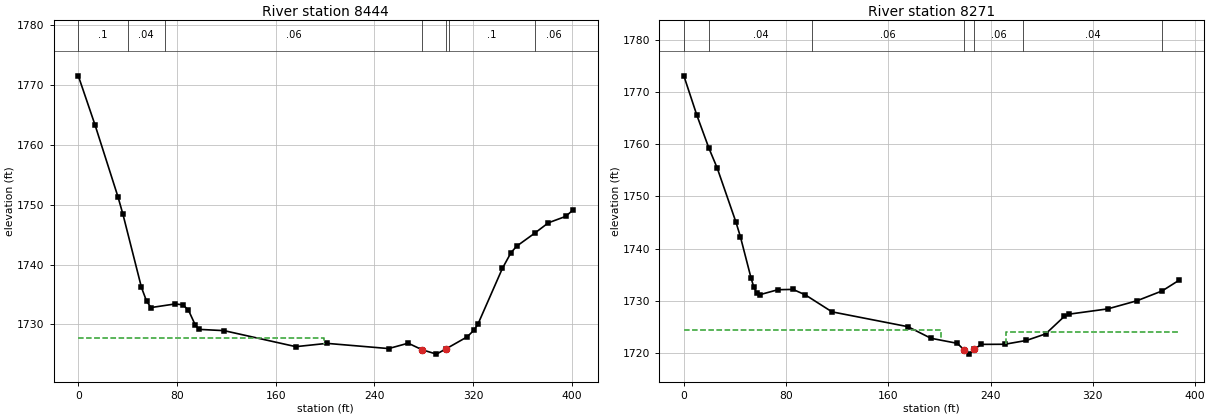
Type RM Length L Ch R = 1 ,8444    ,152,172.5,188.6
XS GIS Cut Line= 2
2028988.91272256212347.0661210772029251.67075065212650.137709646
#Sta/Elev= 30
       0 1771.58    13.5  1763.4    32.1 1751.37    36.2  1748.4    51.2 1736.17
    55.3  1733.9    58.9 1732.81    78.6 1733.42    84.9 1733.26    89.3 1732.36
    94.9 1729.84      98 1729.16   118.1 1728.95   176.3 1726.27   201.5 1726.82
   251.5 1725.95   267.3 1726.85   278.6 1725.75   290.2 1725.02   297.7 1725.87
   315.1 1727.91   320.5    1729   323.8 1730.02   343.7 1739.39   350.7 1742.02
   355.3 1743.09     370 1745.28   380.9 1746.99   394.9 1748.06   401.1 1749.17
#Mann= 7 ,-1 , 0
       0      .1       0      40     .04       0      70     .06       0
   278.6    .045       0   297.7     .06       0     300      .1       0
     370     .06       0
#XS Ineff= 2 , 0
          199.45  1727.8
Permanent Ineff=
       F       F
Bank Sta=278.6,297.7
XS Rating Curve= 0 ,0
Exp/Cntr(USF)=0,0
Exp/Cntr=0.5,0.3

Type RM Length L Ch R = 1 ,8271    ,56.5,55.6,54.8
XS GIS Cut Line= 4
2028970.29458793212360.5672356832029073.07893261212502.572427339
2028989.13043356212600.0781880072028987.98417614212683.427315675
#Sta/Elev= 30
       0 1773.09    10.2 1765.52    19.6 1759.23    26.1 1755.42    40.8 1745.03
    44.2  1742.3    52.5 1734.42    54.8 1732.54    57.2 1731.47    59.5 1731.16
    73.6 1732.11    85.4 1732.17      95 1731.13   115.9 1727.87   175.3 1725.03
   193.3 1722.81   213.9 1721.84   219.11720.632   223.2 1719.77   227.31720.727
   232.8 1721.64   251.1 1721.66     268 1722.39   283.1 1723.65   297.6 1726.98
   301.5 1727.43   331.7 1728.44   354.6    1730   374.3 1731.89   387.3  1733.9
#Mann= 7 ,-1 , 0
       0      .1       0      20     .04       0     100     .06       0
   219.1    .045       0   227.3     .06       0   265.3     .04       0
  373.97     .06       0
#XS Ineff= 2 , 0
          200.84 1724.47     252            1724
Permanent Ineff=
       F       F
Bank Sta=219.1,227.3
XS Rating Curve= 0 ,0
Exp/Cntr(USF)=0,0
Exp/Cntr=0.5,0.3