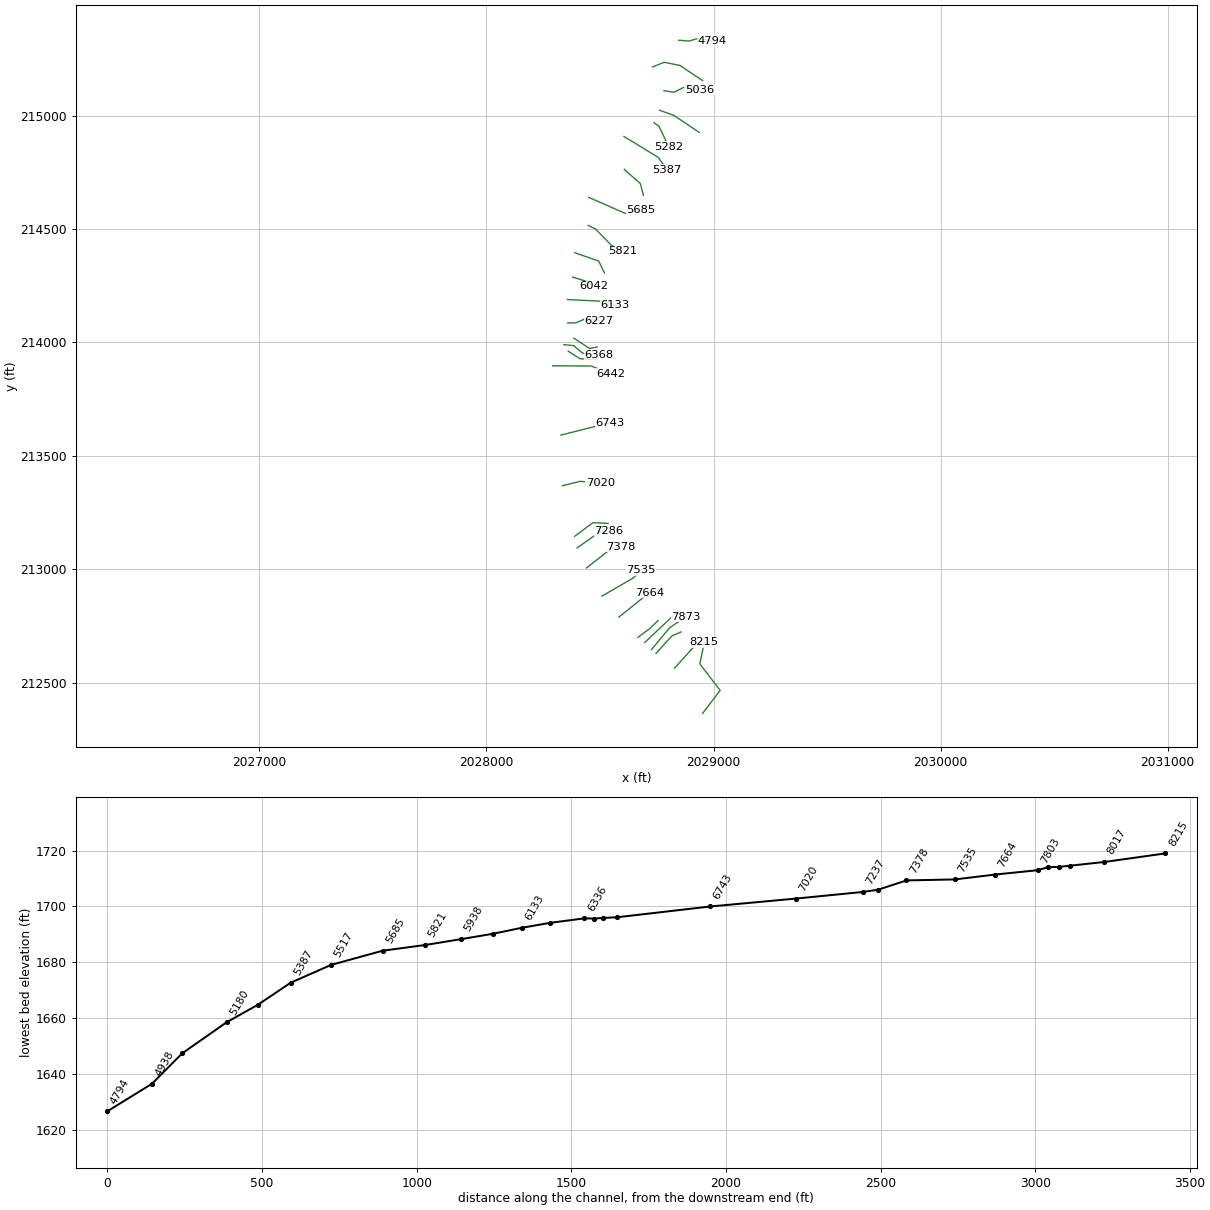
HEC-RAS study SPRUCERN.prj: SPRUCERN

--- SPRUCERN.g01 (geometry) --- (continued)

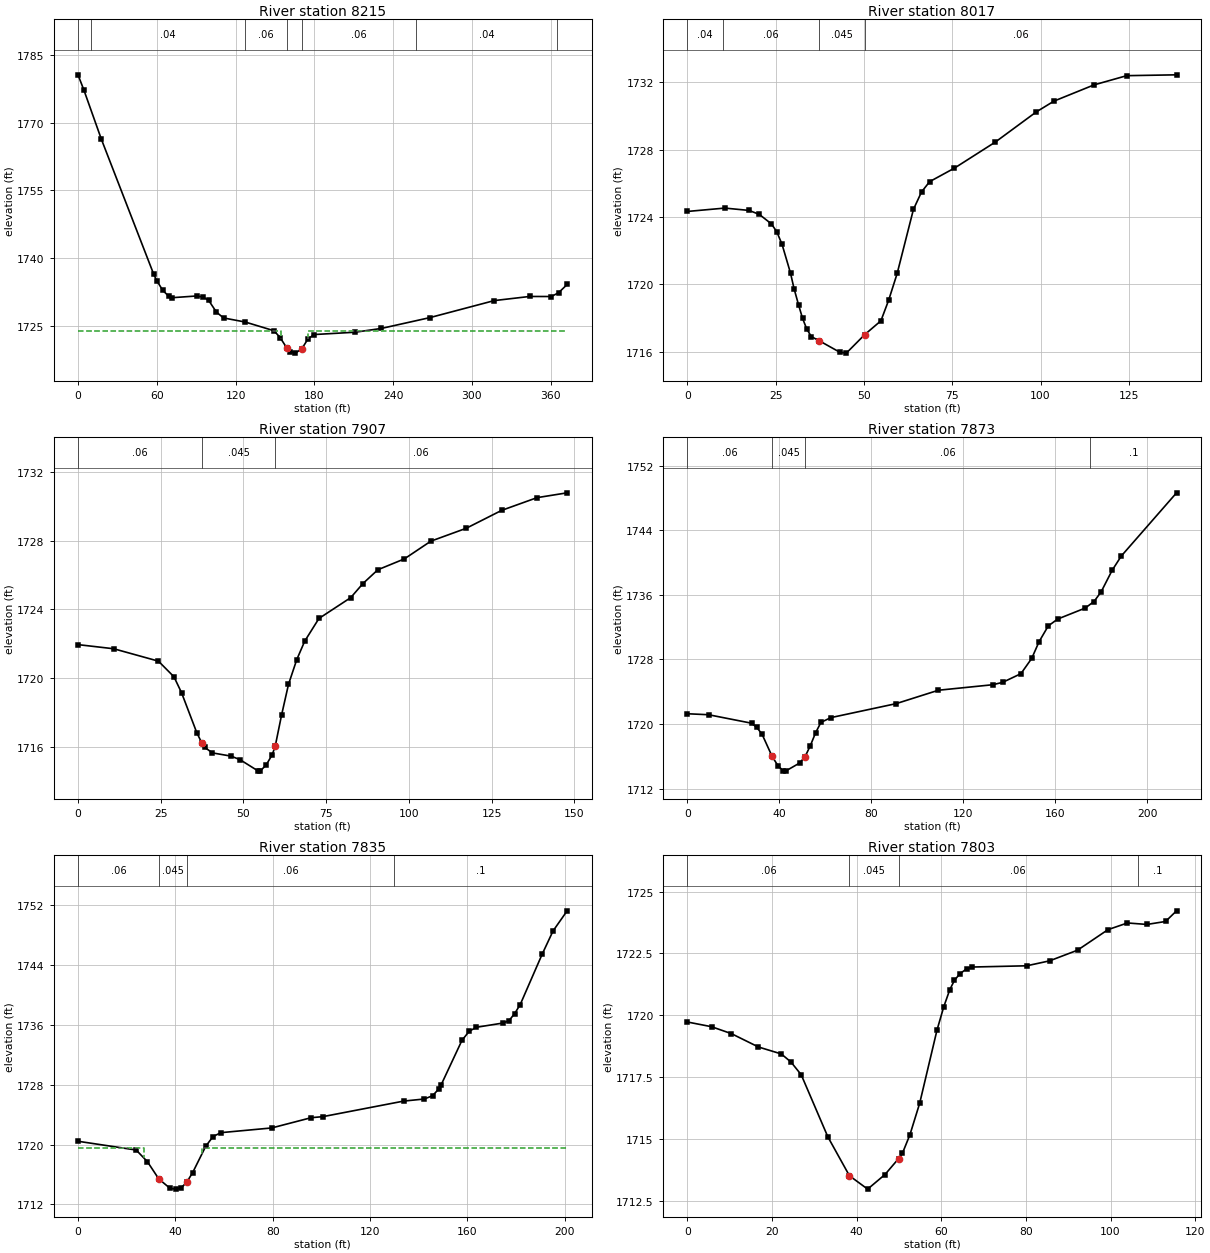
Type RM Length L Ch R = 1 ,8215    ,210.7,198.1,180.3
XS GIS Cut Line= 4
2028951.87266076212364.9752457062029029.22679559212466.202703094
2028939.62430682212582.9171378942028959.31090686212678.911222641
#Sta/Elev= 30
       0  1780.6     4.5 1777.22    17.8 1766.34    57.6  1736.5      60 1735.03
    64.6 1732.87    69.3 1731.54    71.7 1731.27    90.4 1731.65    95.4 1731.39
    99.5 1730.67   105.4 1728.09   110.8 1726.79   127.4 1725.88   149.3 1723.95
   153.9 1722.45   159.21720.057   161.5 1719.33   165.6    1719   170.51719.995
   174.9 1722.03   179.6 1723.11   211.1 1723.63   231.1 1724.47   267.8 1726.85
     317 1730.63   343.9 1731.54   360.5 1731.53     366 1732.38   372.5  1734.2
#Mann= 7 ,-1 , 0
       0      .1       0      10     .04       0   127.4     .06       0
   159.2    .045       0   170.5     .06       0   257.4     .04       0
  364.54     .06       0
#XS Ineff= 2 , 0
           154.5  1723.9   175.5          1723.9
Permanent Ineff=
       F       F
Bank Sta=159.2,170.5
XS Rating Curve= 0 ,0
Exp/Cntr(USF)=0,0
Exp/Cntr=0.5,0.3

Type RM Length L Ch R = 1 ,8017    ,108.6,110,108.6
XS GIS Cut Line= 2
2028828.34413514212564.1799121982028921.00050524212667.129147885
#Sta/Elev= 30
       0 1724.33    10.6 1724.53    17.5 1724.39    20.4 1724.15    23.8 1723.59
    25.3 1723.13    26.8 1722.38    29.2 1720.67    30.2 1719.75    31.5 1718.77
    32.6 1717.99    33.8 1717.35    35.1  1716.9    37.41716.646    43.1 1715.98
      45 1715.92    50.21717.016    54.8 1717.84      57 1719.07    59.4 1720.65
      64 1724.45    66.3 1725.49    68.6  1726.1    75.6  1726.9    87.2 1728.45
    98.8 1730.24   103.8 1730.88   115.1 1731.84   124.4 1732.39   138.5 1732.44
#Mann= 4 ,-1 , 0
       0     .04       0      10     .06       0    37.4    .045       0
    50.2     .06       0
Bank Sta=37.4,50.2
XS Rating Curve= 0 ,0
Exp/Cntr(USF)=0,0
Exp/Cntr=0.3,0.1

Type RM Length L Ch R = 1 ,7907    ,28.2,34.6,32.5
XS GIS Cut Line= 3
 2028746.7975537212629.5830359072028816.62639953212706.610731815
   2028856.93996212723.887972019
#Sta/Elev= 30
       0 1721.95    10.8 1721.71    24.3 1720.99      29 1720.08    31.3 1719.15
    35.9 1716.83    37.4 1716.24    38.3 1715.98    40.6 1715.66    46.3 1715.47
      49 1715.26    54.5  1714.6    55.1 1714.62    56.8 1714.94    58.7 1715.56
    59.6 1716.06    61.5 1717.85    63.6 1719.64    66.1 1721.08    68.5 1722.15
    72.8 1723.47    82.4 1724.68    86.1  1725.5    90.6  1726.3    98.6 1726.93
   106.6 1727.96   117.3 1728.71     128 1729.75   138.7 1730.49   147.8 1730.77
#Mann= 3 ,-1 , 0
       0     .06       0    37.4    .045       0    59.6     .06       0
Bank Sta=37.4,59.6
XS Rating Curve= 0 ,0
Exp/Cntr(USF)=0,0
Exp/Cntr=0.5,0.3

Type RM Length L Ch R = 1 ,7873    ,39.6,38.2,36.9
XS GIS Cut Line= 3
2028726.21806407212645.3000812012028805.97811541  212741.8517223
2028878.18195136212791.386912082
#Sta/Elev= 30
       0 1721.28     9.2 1721.16    27.9 1720.11    30.2 1719.59    32.5 1718.74
    36.8 1716.04    39.5  1714.8    41.8 1714.21    42.7 1714.18    48.8 1715.18
    51.2 1715.97    53.5 1717.34    55.8 1718.94    58.1 1720.21    62.4  1720.8
    90.8 1722.53   109.2 1724.19   132.8 1724.87   137.1 1725.16   145.1 1726.24
   149.8 1728.13     153  1730.2     157 1732.15   161.1    1733     173 1734.35
   176.9 1735.17     180 1736.37   184.8 1739.04   188.8 1740.81   212.8 1748.62
#Mann= 4 ,-1 , 0
       0     .06       0    36.8    .045       0    51.2     .06       0
  175.24      .1       0
#XS Ineff= 2 , 0
              27  1719.7      60          1719.7
Permanent Ineff=
       F       F
Bank Sta=36.8,51.2
XS Rating Curve= 0 ,0
Exp/Cntr(USF)=0,0
Exp/Cntr=0.5,0.3

Type RM Length L Ch R = 1 ,7835    ,33.2,32,30.8
XS GIS Cut Line= 2
2028696.61428292212677.0755601872028842.91961287212814.895137741
#Sta/Elev= 30
       0 1720.44    23.9 1719.27    28.5 1717.72    33.21715.405    37.8 1714.15
    40.1 1714.04    42.5 1714.23    44.8 1715.03    47.1 1716.24    52.5 1719.78
    55.5 1721.07    58.7 1721.59    79.6 1722.22    95.8 1723.59   100.6 1723.73
   133.8 1725.81   142.3 1726.09   145.7 1726.53   148.2 1727.42   149.2 1727.97
   157.8 1733.95   160.8 1735.16   163.7 1735.68   174.7 1736.25   177.1 1736.57
   179.4  1737.5   181.7 1738.71   190.7 1745.43   195.2 1748.56     201 1751.25
#Mann= 4 ,-1 , 0
       0     .06       0    33.2    .045       0    44.8     .06       0
     130      .1       0
#XS Ineff= 2 , 0
              27  1719.6      51          1719.6
Permanent Ineff=
       F       F
Bank Sta=33.2,44.8
XS Rating Curve= 0 ,0
Exp/Cntr(USF)=0,0
Exp/Cntr=0.5,0.3

Type RM Length L Ch R = 1 ,7803    ,135,138.1,135.5
XS GIS Cut Line= 3
2028666.84126097 212699.738606752028720.07993161212739.576658088
2028755.15817726212773.996157341
#Sta/Elev= 30
       0 1719.73     5.7 1719.54    10.4 1719.26    16.8 1718.72    22.2 1718.44
    24.5 1718.11    26.9  1717.6    33.2 1715.09    38.3 1713.52    42.6 1712.98
    46.7 1713.57    49.9 1714.21    50.8 1714.42    52.6 1715.18    54.9 1716.45
      59 1719.41    60.6 1720.35      62 1721.03    63.1 1721.41    64.4 1721.68
    66.1 1721.89    67.3 1721.95    80.2    1722    85.6  1722.2    92.2 1722.63
    99.4 1723.46     104 1723.73   108.6 1723.67     113 1723.79   115.6 1724.22
#Mann= 4 ,-1 , 0
       0     .06       0    38.3    .045       0    49.9     .06       0
  106.49      .1       0
Bank Sta=38.3,49.9
XS Rating Curve= 0 ,0
Exp/Cntr(USF)=0,0
Exp/Cntr=0.3,0.1

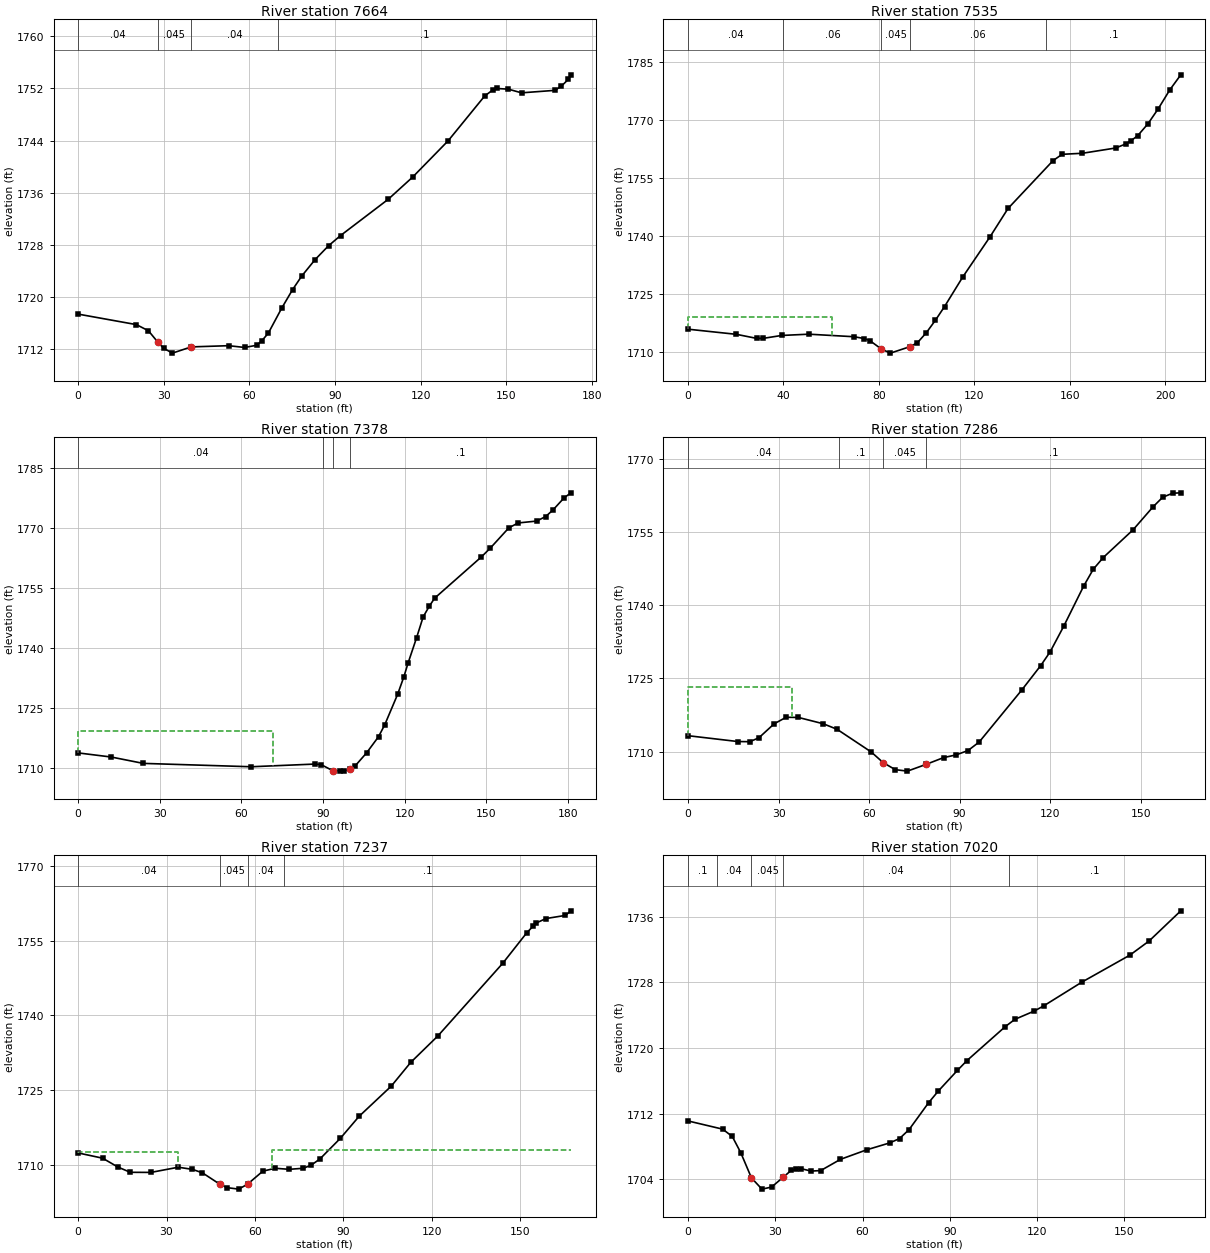
Type RM Length L Ch R = 1 ,7664    ,129.8,129.3,125.9
XS GIS Cut Line= 2
2028583.29905011212789.502046079 2028717.9442091212897.484797351
#Sta/Elev= 30
       0  1717.4    20.4 1715.79    24.6 1714.85    27.81713.159    29.9 1712.18
      33 1711.42    39.61712.375    52.7 1712.56    58.3 1712.29    62.5 1712.62
    64.3  1713.3    66.6 1714.48    71.3 1718.32    75.1 1721.15    78.3 1723.23
      83 1725.76    87.7 1727.88    91.9 1729.44   108.6    1735   117.2 1738.42
   129.6 1743.97   142.4 1750.84   145.3 1751.78   146.6 1751.99   150.7 1751.88
   155.3 1751.32     167  1751.7   169.3 1752.36   171.7 1753.39   172.6 1754.08
#Mann= 4 ,-1 , 0
       0     .04       0    27.8    .045       0    39.6     .04       0
      70      .1       0
Bank Sta=27.8,39.6
XS Rating Curve= 0 ,0
Exp/Cntr(USF)=0,0
Exp/Cntr=0.3,0.1

Type RM Length L Ch R = 1 ,7535    ,155.9,156.9,157.5
XS GIS Cut Line= 3
2028509.53305541212882.3760996422028648.32456573212962.979354327
 2028680.9548762212995.366958763
#Sta/Elev= 30
       0 1715.87    20.3 1714.54    28.7  1713.5    31.6 1713.51    39.2 1714.25
    50.6 1714.58    69.6 1713.92    73.8 1713.46    76.2 1712.91      81 1710.75
    84.8 1709.68      93 1711.35    96.1 1712.35    99.9 1714.99   103.7 1718.21
   107.5 1721.73   115.1 1729.35   126.6 1739.81   134.1  1747.1     153  1759.5
   156.8 1761.11   165.3 1761.38   179.2 1762.74   183.4 1763.78   185.7 1764.66
   188.4  1765.9   192.7 1768.97     197 1772.84   201.9 1777.78   206.5 1781.67
#Mann= 5 ,-1 , 0
       0     .04       0      40     .06       0      81    .045       0
      93     .06       0     150      .1       0
#XS Ineff= 2 , 0
           60.39 1719.13
Permanent Ineff=
       F       F
Bank Sta=81,93
XS Rating Curve= 0 ,0
Exp/Cntr(USF)=0,0
Exp/Cntr=0.3,0.1

Type RM Length L Ch R = 1 ,7378    ,92.7,91.8,91.1
XS GIS Cut Line= 3
2028440.21079534213005.9119220852028544.49723584213087.339295393
2028591.84213444213099.265872903
#Sta/Elev= 30
       0 1713.86    12.2 1712.83    23.9 1711.25    63.6 1710.41      87 1711.08
    89.3 1710.94    93.5 1709.46    96.3 1709.32    97.7 1709.38     1001709.934
   101.9  1710.7     106 1713.87   110.4 1717.91   112.7 1720.91   117.4 1728.45
   119.7 1732.82   121.2 1736.16   124.4 1742.62   126.8 1747.78   129.1 1750.48
     131 1752.42   148.2 1762.72   151.5 1764.93   158.3 1769.97   161.7 1771.18
   168.5 1771.65   171.8 1772.77   174.5 1774.41   178.6 1777.44   181.1 1778.69
#Mann= 4 ,-1 , 0
       0     .04       0      90      .1       0    93.5    .045       0
     100      .1       0
#XS Ineff= 2 , 0
           71.55  1719.2
Permanent Ineff=
       F       F
Bank Sta=93.5,100
XS Rating Curve= 0 ,0
Exp/Cntr(USF)=0,0
Exp/Cntr=0.3,0.1

Type RM Length L Ch R = 1 ,7286    ,49.4,49.4,49.6
XS GIS Cut Line= 3
2028398.76758475213094.0655812972028498.82752419213164.751800343
2028539.52367046213166.807161266
#Sta/Elev= 30
       0 1713.26    16.5 1712.06    20.5 1712.03    23.5 1712.84    28.5 1715.68
    32.5 1717.04    36.6    1717    44.8 1715.71    49.4 1714.57    60.7 1709.92
    64.7 1707.72    68.7 1706.29    72.7 1705.99      79  1707.4    84.7 1708.77
    88.8 1709.31    92.8 1710.22    96.5 1711.97   110.6 1722.63   116.9 1727.66
     120 1730.46   124.5 1735.71   131.1 1743.94   134.3 1747.41   137.6 1749.81
   147.5 1755.51   154.1 1760.21   157.3 1762.18   160.6 1763.01   163.3 1763.09
#Mann= 4 ,-1 , 0
       0     .04       0      50      .1       0    64.7    .045       0
      79      .1       0
#XS Ineff= 2 , 0
           34.37 1723.15
Permanent Ineff=
       F       F
Bank Sta=64.7,79
XS Rating Curve= 0 ,0
Exp/Cntr(USF)=0,0
Exp/Cntr=0.3,0.1

Type RM Length L Ch R = 1 ,7237    ,220,216.9,212.1
XS GIS Cut Line= 3
2028388.30889094213145.3150971532028468.77900227213205.546389405
2028535.49282795213202.486122172
#Sta/Elev= 30
       0 1712.44     8.3 1711.39    13.5 1709.61    17.7 1708.56    24.7 1708.54
      34 1709.58    38.8 1709.15    42.2 1708.45    48.1 1706.17    50.5 1705.49
    54.5 1705.19    57.5 1706.18    62.7 1708.79    66.9 1709.37    71.6 1709.16
    76.3 1709.36      79 1709.94    82.1 1711.25      89 1715.36    95.4 1719.79
   106.3 1725.83   112.9 1730.58   122.1 1735.87   144.1 1750.41   152.3 1756.55
   154.4 1757.85   155.6 1758.54   158.8 1759.41   165.4 1760.04   167.3 1760.96
#Mann= 4 ,-1 , 0
       0     .04       0    48.1    .045       0    57.5     .04       0
      70      .1       0
#XS Ineff= 2 , 0
            33.8 1712.68   65.89         1712.95
Permanent Ineff=
       F       F
Bank Sta=48.1,57.5
XS Rating Curve= 0 ,0
Exp/Cntr(USF)=0,0
Exp/Cntr=0.3,0.1

Type RM Length L Ch R = 1 ,7020    ,274.5,276.6,277
XS GIS Cut Line= 3
2028335.10023529213368.7391174152028413.08213862213387.938316497
2028501.82988838213379.981621691
#Sta/Elev= 30
       0 1711.12    11.9 1710.12    15.2 1709.23    18.1 1707.27    21.81704.178
    25.4 1702.81    28.7 1703.06    32.81704.284    35.5 1705.11      37 1705.21
    38.9  1705.3    42.3 1705.01    45.6 1705.07    52.4 1706.44    61.4  1707.6
    69.3 1708.44    72.7 1708.97      76 1710.07    82.7 1713.34      86 1714.75
    92.6 1717.28    95.9 1718.48   109.1 1722.63   112.4 1723.51     119 1724.51
   122.3 1725.15   135.4 1728.04   151.9 1731.33   158.5 1733.05   169.4 1736.73
#Mann= 5 ,-1 , 0
       0      .1       0      10     .04       0    21.8    .045       0
    32.8     .04       0  110.31      .1       0
Bank Sta=21.8,32.8
XS Rating Curve= 0 ,0
Exp/Cntr(USF)=0,0
Exp/Cntr=0.3,0.1

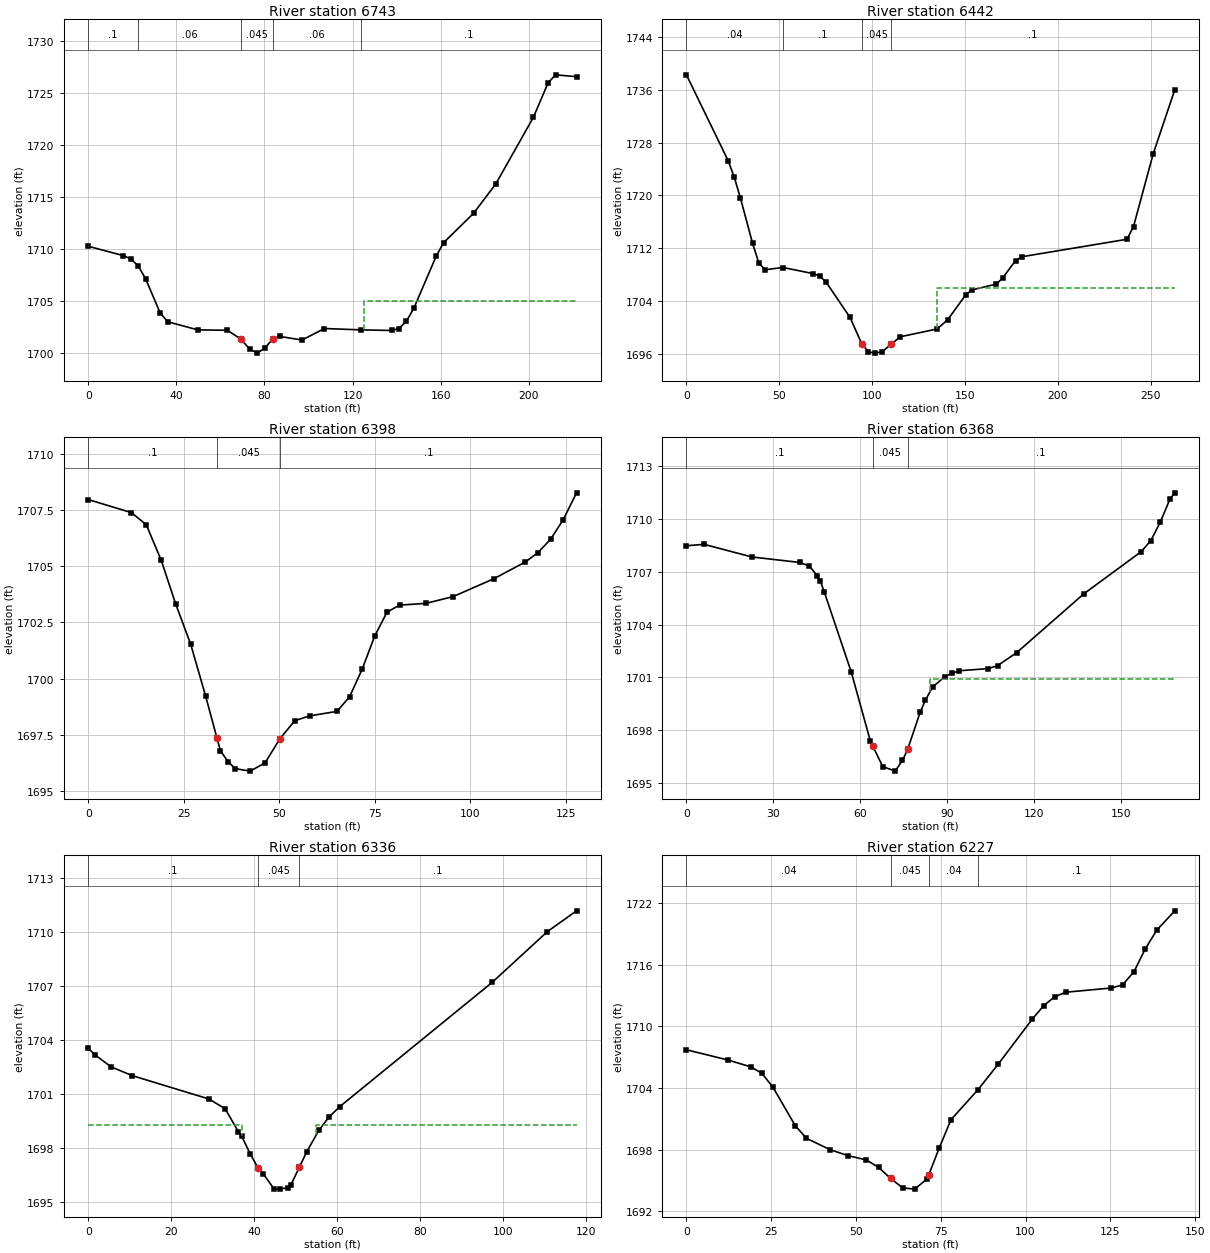
Type RM Length L Ch R = 1 ,6743    ,301.4,301.7,295
XS GIS Cut Line= 2
2028328.00670954213591.7521142222028542.83746931213646.224870971
#Sta/Elev= 30
       0 1710.27    15.8 1709.38    19.2 1709.07    22.6 1708.41      26 1707.16
    32.7 1703.83    36.1    1703    49.7 1702.22    63.2 1702.18    69.21701.336
    73.3 1700.37    76.7 1699.98    80.1 1700.45    83.91701.387    86.9 1701.59
      97 1701.24   107.2 1702.35   123.8 1702.22   137.7 1702.16     141 1702.35
   144.4 1703.05   147.8 1704.32     158 1709.36   161.3 1710.62   174.9 1713.45
     185 1716.29     202 1722.68   208.7 1726.01   212.1 1726.78   221.6  1726.6
#Mann= 5 ,-1 , 0
       0      .1       0    22.6     .06       0    69.2    .045       0
    83.9     .06       0   123.8      .1       0
#XS Ineff= 2 , 0
                             125            1705
Permanent Ineff=
       F       F
Bank Sta=69.2,83.9
XS Rating Curve= 0 ,0
Exp/Cntr(USF)=0,0
Exp/Cntr=0.3,0.1

Type RM Length L Ch R = 1 ,6442    ,50,43.7,35
XS GIS Cut Line= 3
2028291.28350275213897.166784085 2028460.8040483213896.365675645
2028547.73389688213862.279737628
#Sta/Elev= 30
       0 1738.28    22.5 1725.25    25.8 1722.73    29.1 1719.59    35.6 1712.77
    38.9 1709.84    42.2 1708.75      52 1709.09    68.4 1708.16    71.7 1707.78
      75 1706.96    88.1 1701.52    94.51697.464      98 1696.32   101.3 1696.12
   105.3  1696.3   110.41697.519   115.2  1698.6     135 1699.78   140.6 1701.16
   150.5    1705   153.7 1705.69   166.9 1706.59   170.2 1707.49   177.2 1710.14
   180.8 1710.73   237.2 1713.37   240.7  1715.3   251.3 1726.32   262.9 1736.01
#Mann= 4 ,-1 , 0
       0     .04       0      52      .1       0    94.5    .045       0
   110.4      .1       0
#XS Ineff= 2 , 0
                             135            1706
Permanent Ineff=
       F       F
Bank Sta=94.5,110.4
XS Rating Curve= 0 ,0
Exp/Cntr(USF)=0,0
Exp/Cntr=0.3,0.1

Type RM Length L Ch R = 1 ,6398    ,32.3,30.4,30.8
XS GIS Cut Line= 3
2028360.07617066 213961.519506682028411.89172877213928.439517604
2028478.05170692213924.048368612
#Sta/Elev= 30
       0 1707.97    11.3 1707.39    15.2 1706.85    19.1 1705.27    22.9 1703.32
    26.8 1701.54    30.7 1699.24    33.7 1697.35    34.6 1696.79    36.6  1696.3
    38.5 1695.99    42.4 1695.88    46.3 1696.25    50.2 1697.33    54.1 1698.13
      58 1698.34    65.1 1698.54    68.4 1699.19    71.7 1700.42      75  1701.9
    78.2 1702.96    81.5 1703.27    88.4 1703.35    95.5 1703.65   106.1 1704.44
   114.4 1705.19   117.7 1705.61     121  1706.2   124.3 1707.07   127.8 1708.27
#Mann= 3 ,-1 , 0
       0      .1       0    33.7    .045       0    50.2      .1       0
Bank Sta=33.7,50.2
XS Rating Curve= 0 ,0
Exp/Cntr(USF)=0,0
Exp/Cntr=0.5,0.3

Type RM Length L Ch R = 1 ,6368    ,29.8,31.2,32.3
XS GIS Cut Line= 4
2028340.53827508213990.6679780152028384.18824317213986.058776731
2028424.14805557213952.3541863522028495.97739048213944.373149141
#Sta/Elev= 30
       0 1708.48     6.1 1708.56    22.6 1707.84    39.1 1707.53    42.4 1707.32
    45.2 1706.76    46.2 1706.46    47.5 1705.87    56.8 1701.32    63.4 1697.39
    64.3 1697.07    67.7 1695.92      72 1695.66    74.5 1696.27    76.3  1696.9
    80.6 1699.01    82.4 1699.69    84.9 1700.45    89.2 1701.04    91.7 1701.23
    94.1 1701.37     104 1701.49   107.3 1701.66   113.9  1702.4     137 1705.74
   156.8 1708.14   160.1 1708.76   163.4 1709.82   166.7 1711.12   168.4 1711.49
#Mann= 3 ,-1 , 0
       0      .1       0    64.3    .045       0    76.3      .1       0
#XS Ineff= 2 , 0
              56  1700.9      84          1700.9
Permanent Ineff=
       F       F
Bank Sta=64.3,76.3
XS Rating Curve= 0 ,0
Exp/Cntr(USF)=0,0
Exp/Cntr=0.5,0.3

Type RM Length L Ch R = 1 ,6336    ,100.9,109.5,120.8
XS GIS Cut Line= 3
 2028384.6629241214019.1428661772028453.97193147213973.356915857
2028487.99635327213979.937771102
#Sta/Elev= 23
       0 1703.55     1.6 1703.19     5.5 1702.52    10.6 1702.03    29.1 1700.73
      33 1700.19    36.2 1698.91      37 1698.66      39  1697.7    40.9 1696.91
    42.2 1696.57    44.8 1695.73    46.2 1695.72    48.2 1695.81    48.8 1695.93
    50.91696.942    52.7 1697.81    55.6 1698.99      58 1699.72    60.6  1700.3
    97.4 1707.22   110.7 1710.04   117.7 1711.19
#Mann= 3 ,-1 , 0
       0      .1       0    40.9    .045       0    50.9      .1       0
#XS Ineff= 2 , 0
              37  1699.3      55          1699.3
Permanent Ineff=
       F       F
Bank Sta=40.9,50.9
XS Rating Curve= 0 ,0
Exp/Cntr(USF)=0,0
Exp/Cntr=0.5,0.3

Type RM Length L Ch R = 1 ,6227    ,98.3,93.4,87.9
XS GIS Cut Line= 4
 2028357.1752415214085.8880097422028393.71795374214086.691146274
2028439.25562046214106.0030729892028496.23604802214095.119171097
#Sta/Elev= 30
       0 1707.73    12.4 1706.72      19 1706.06    22.2 1705.45    25.5 1704.09
    32.1 1700.33    35.4  1699.1    42.4 1697.99    47.7 1697.41    53.1 1696.99
    56.7 1696.26    60.2 1695.19    63.8 1694.27    67.3 1694.15    70.9 1695.13
    71.5 1695.57    74.5 1698.12      78 1700.91      86 1703.85    91.9 1706.31
   101.9 1710.68   105.3 1712.01   108.6  1712.9   111.9 1713.34   125.3 1713.75
   128.6 1714.05     132 1715.35   135.3 1717.56   138.7 1719.39     144 1721.27
#Mann= 4 ,-1 , 0
       0     .04       0    60.2    .045       0    71.5     .04       0
   86.01      .1       0
Bank Sta=60.2,71.5
XS Rating Curve= 0 ,0
Exp/Cntr(USF)=0,0
Exp/Cntr=0.3,0.1

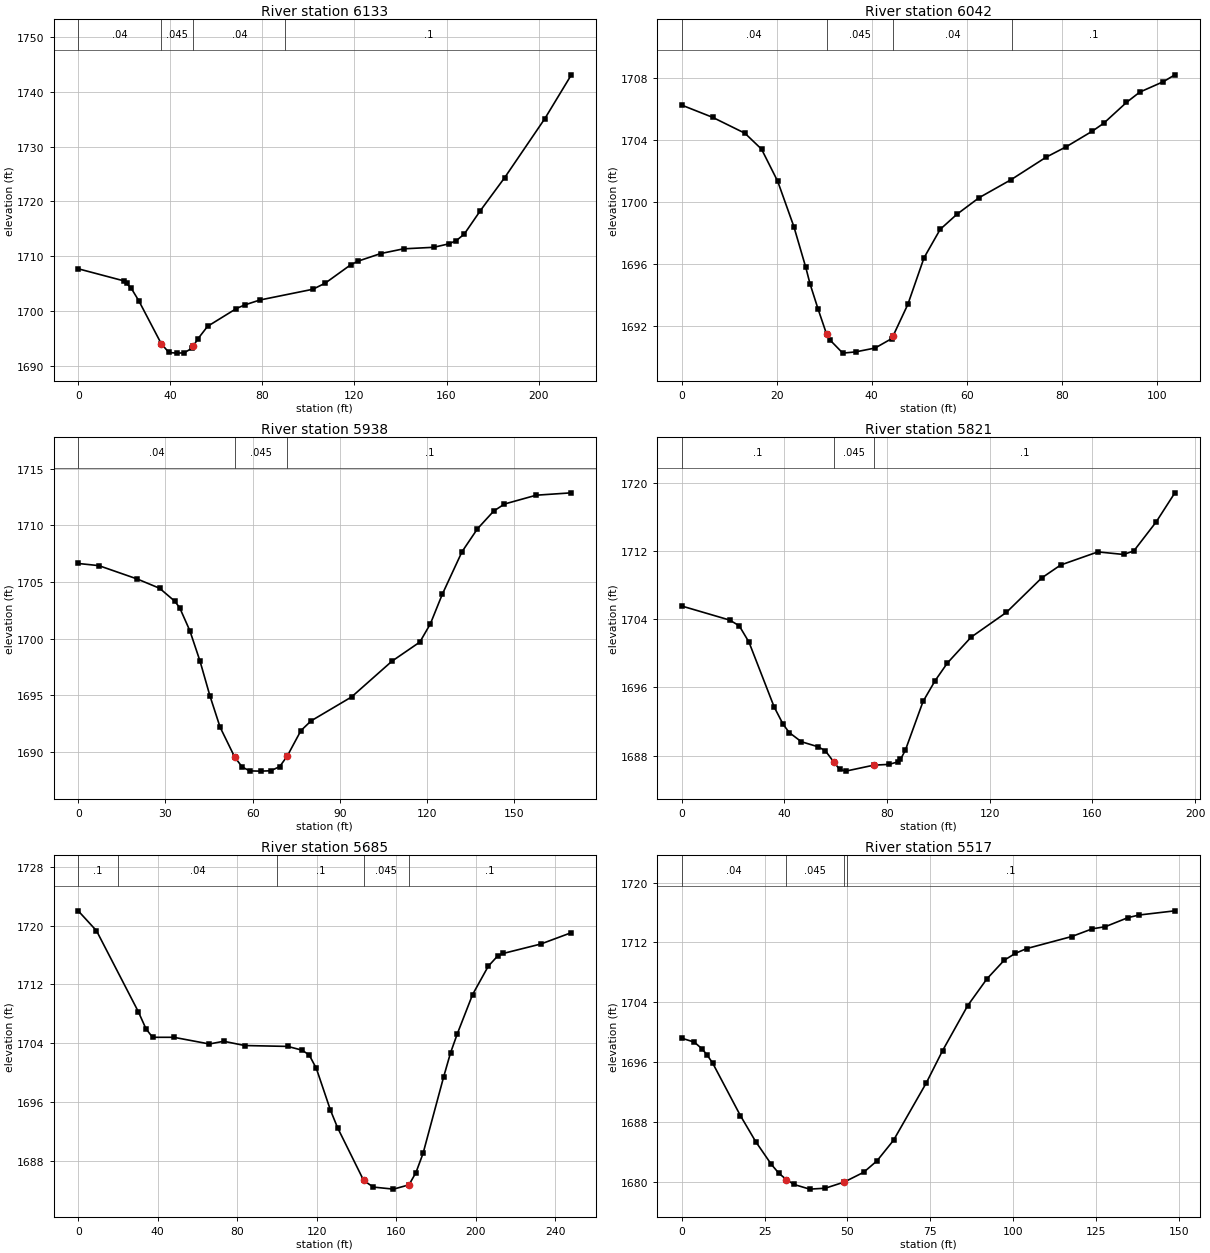
Type RM Length L Ch R = 1 ,6133    ,94.8,91.9,89
XS GIS Cut Line= 3
2028356.42135314214189.2548994672028521.41559868214181.159583316
2028567.31960717214164.022086811
#Sta/Elev= 30
       0 1707.72    19.7 1705.53      21 1705.04      23 1704.19    26.3  1701.9
    36.11694.033    39.4 1692.45    42.7 1692.33      46 1692.38    49.3  1693.2
      501693.626      52 1694.94    56.2 1697.22    68.7 1700.46    72.3 1701.12
    78.9 1702.02   101.9 1703.98   107.3  1705.1   118.3 1708.43   121.6 1709.12
   131.4  1710.5   141.3 1711.36   154.4 1711.64     161 1712.27   164.3 1712.88
   167.7 1714.06   174.7 1718.34   185.2 1724.33   202.7 1735.13   214.2 1743.11
#Mann= 4 ,-1 , 0
       0     .04       0    36.1    .045       0      50     .04       0
      90      .1       0
Bank Sta=36.1,50
XS Rating Curve= 0 ,0
Exp/Cntr(USF)=0,0
Exp/Cntr=0.3,0.1

Type RM Length L Ch R = 1 ,6042    ,103.8,103.3,102.7
XS GIS Cut Line= 3
2028379.78283175214287.938749055 2028436.8283226214270.717489937
2028474.29360581214247.242407424
#Sta/Elev= 30
       0 1706.27     6.5 1705.48    13.3 1704.45    16.8 1703.42    20.2 1701.34
    23.6 1698.41    26.1 1695.78      27 1694.71    28.7 1693.07    30.5 1691.44
    31.3 1691.04    33.9 1690.22    36.6  1690.3    40.7 1690.55    44.2 1691.16
    44.5 1691.34    47.6 1693.38      51 1696.39    54.4 1698.23    57.9  1699.2
    62.6 1700.28    69.3 1701.44    76.7  1702.9    80.9 1703.57    86.4 1704.58
    88.8 1705.09    93.6 1706.44    96.4 1707.11   101.4 1707.79   103.8 1708.23
#Mann= 4 ,-1 , 0
       0     .04       0    30.5    .045       0    44.5     .04       0
   69.59      .1       0
Bank Sta=30.5,44.5
XS Rating Curve= 0 ,0
Exp/Cntr(USF)=0,0
Exp/Cntr=0.3,0.1

Type RM Length L Ch R = 1 ,5938    ,123.6,117.2,111.5
XS GIS Cut Line= 3
2028389.12550408214395.6950816352028494.38966409214358.820684909
2028519.62899103214306.477022175
#Sta/Elev= 30
       0 1706.63     7.1 1706.44    20.3 1705.26      28 1704.44    33.2  1703.3
    34.9 1702.72    38.4 1700.69    41.9    1698    45.3 1694.94    48.8 1692.17
    53.8 1689.54    56.4 1688.65      59 1688.31    62.7 1688.29    66.2 1688.32
    69.3 1688.69    71.91689.624    76.6 1691.87    80.1 1692.73      94 1694.84
   107.9    1698   117.5 1699.69   121.1 1701.29   125.2  1703.9     132 1707.67
   137.3 1709.69   142.9 1711.26   146.6 1711.88   157.5 1712.66   169.6 1712.87
#Mann= 3 ,-1 , 0
       0     .04       0    53.8    .045       0    71.9      .1       0
Bank Sta=53.8,71.9
XS Rating Curve= 0 ,0
Exp/Cntr(USF)=0,0
Exp/Cntr=0.3,0.1

Type RM Length L Ch R = 1 ,5821    ,130.7,136.3,143.2
XS GIS Cut Line= 4
2028447.97973736214516.2696726932028480.70011462214499.909484064
2028551.59426534214427.0322801742028599.18754135214401.748352293
#Sta/Elev= 30
       0 1705.54    18.7 1703.89    22.4 1703.22    26.2  1701.3      36  1693.7
    39.5 1691.66    41.9 1690.69    46.6 1689.62    53.2 1689.02      56 1688.54
    59.2 1687.25    61.5 1686.38    63.9 1686.17    74.8 1686.87    80.7 1686.96
    84.2 1687.25    85.2 1687.54    87.1 1688.61      94 1694.34    98.7 1696.78
   103.5 1698.86   112.7 1701.88   126.5  1704.8   140.2 1708.83   147.6 1710.35
   162.1 1711.89   172.1 1711.59   176.1    1712   184.8  1715.4   192.1 1718.82
#Mann= 3 ,-1 , 0
       0      .1       0    59.2    .045       0    74.8      .1       0
Bank Sta=59.2,74.8
XS Rating Curve= 0 ,0
Exp/Cntr(USF)=0,0
Exp/Cntr=0.3,0.1

Type RM Length L Ch R = 1 ,5685    ,170.7,167.2,163.2
XS GIS Cut Line= 3
2028450.19244926214639.7997250132028613.24348744214568.189471758
2028680.99780398214585.816611021
#Sta/Elev= 30
       0 1722.02     9.2 1719.31    30.2 1708.32    34.1 1705.97    37.4 1704.81
    48.1 1704.81      66  1703.9    73.2 1704.27    83.8 1703.69   105.4 1703.57
   112.6 1703.06   116.2 1702.41   119.8 1700.58   126.9  1694.9   130.5  1692.5
   143.6 1685.34   148.4 1684.43   158.6 1684.15   166.4 1684.73   169.9 1686.39
   173.5 1689.02   183.9 1699.47   187.3 1702.68   190.7 1705.27   198.4 1710.62
   206.3 1714.48   211.1  1715.9   213.8 1716.22   232.7  1717.5   248.1 1719.05
#Mann= 5 ,-1 , 0
       0      .1       0      20     .04       0     100      .1       0
   143.6    .045       0   166.4      .1       0
Bank Sta=143.6,166.4
XS Rating Curve= 0 ,0
Exp/Cntr(USF)=0,0
Exp/Cntr=0.3,0.1

Type RM Length L Ch R = 1 ,5517    ,128,130.2,132.9
XS GIS Cut Line= 3
2028606.62399073214763.1597919952028677.51814145214700.693617232
2028691.39951362214648.142708304
#Sta/Elev= 30
       0 1699.21     3.8 1698.68     6.1  1697.8     7.6    1697     9.3 1695.91
    17.7 1688.87    22.3 1685.41      27 1682.38    29.3 1681.17    31.6 1680.32
    33.9 1679.67    38.6 1679.05    43.3 1679.17      49 1679.99    54.9  1681.3
    58.9 1682.82    63.9 1685.57    73.8 1693.24    78.7 1697.54    86.3 1703.57
    92.1 1707.14    97.3 1709.62   100.7 1710.55   104.1 1711.18   117.7 1712.79
   123.9 1713.82   127.8  1714.1   134.7 1715.32     138 1715.66   148.8 1716.22
#Mann= 4 ,-1 , 0
       0     .04       0    31.6    .045       0      49     .04       0
      50      .1       0
Bank Sta=31.6,49
XS Rating Curve= 0 ,0
Exp/Cntr(USF)=0,0
Exp/Cntr=0.3,0.1

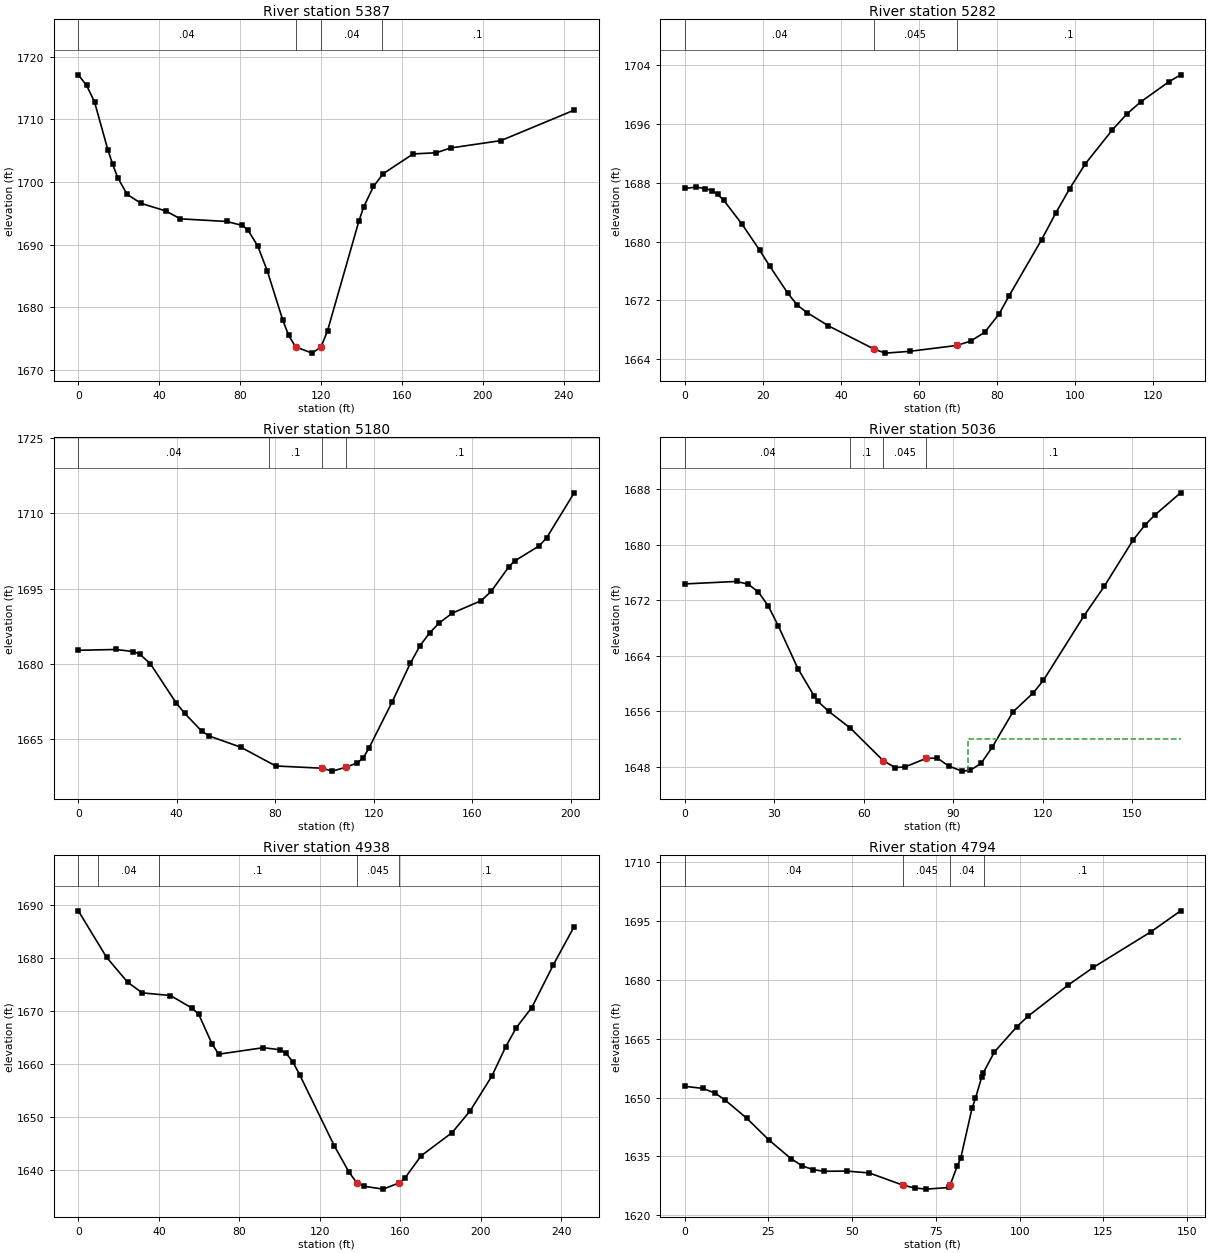
Type RM Length L Ch R = 1 ,5387    ,113.7,105.7,97.5
XS GIS Cut Line= 3
2028605.53161401214908.062750666 2028756.3357237214816.211264115
2028795.97066121214760.296583312
#Sta/Elev= 30
       0 1717.13     4.1 1715.43       8 1712.81    14.6 1705.15      17 1702.82
    19.5 1700.69    24.1 1698.05      31 1696.61    43.2  1695.4    50.4 1694.14
    73.3 1693.72      81 1693.09    83.8 1692.38    88.7 1689.79    93.4 1685.83
   101.1 1677.93     104 1675.52   107.4  1673.7   115.6  1672.7     120  1673.7
   123.2 1676.29   138.7 1693.79   141.1 1696.06   145.9 1699.31   150.7 1701.35
   165.5  1704.5   176.9 1704.69     184 1705.45   208.9 1706.63   245.1 1711.49
#Mann= 4 ,-1 , 0
       0     .04       0   107.4    .045       0     120     .04       0
     150      .1       0
Bank Sta=107.4,120
XS Rating Curve= 0 ,0
Exp/Cntr(USF)=0,0
Exp/Cntr=0.3,0.1

Type RM Length L Ch R = 1 ,5282    ,96.5,102,108.2
XS GIS Cut Line= 3
2028737.91344018214968.6949016342028759.99969483214952.632170981
2028802.96749932214862.680879322
#Sta/Elev= 30
       0 1687.23     2.9 1687.41     5.3 1687.22       7 1686.93     8.4 1686.42
      10 1685.61    14.7 1682.34    19.2 1678.81    21.7 1676.71    26.4 1672.97
    28.8 1671.37    31.3 1670.35    36.8 1668.54    48.5 1665.37    51.4 1664.83
    57.7 1665.08    69.6 1665.87    73.2 1666.46    76.8 1667.66    80.5 1670.15
      83 1672.57    91.4 1680.27      95 1683.87    98.6 1687.22   102.6 1690.59
   109.5 1695.19   113.2 1697.35   116.8 1699.02   124.1 1701.78     127 1702.69
#Mann= 3 ,-1 , 0
       0     .04       0    48.5    .045       0    69.6      .1       0
Bank Sta=48.5,69.6
XS Rating Curve= 0 ,0
Exp/Cntr(USF)=0,0
Exp/Cntr=0.3,0.1

Type RM Length L Ch R = 1 ,5180    ,132.9,143.4,155.1
XS GIS Cut Line= 3
2028761.97247497215023.7408520782028825.32000669215001.156079897
2028936.59132329214926.240738031
#Sta/Elev= 30
       0 1682.65    15.3 1682.81    22.3  1682.4    24.9 1681.89    29.2    1680
    39.7 1672.15    43.2 1670.04    50.1  1666.5    53.1 1665.52      66 1663.27
    80.2 1659.52      99 1659.07   103.2 1658.49   108.6 1659.26   113.3 1660.13
   115.7 1661.11   118.1 1663.14   127.5 1672.35   134.8 1680.01   138.8 1683.57
   142.7 1686.14   146.7 1688.16   151.9 1690.08   163.6 1692.56   167.7 1694.42
   174.8  1699.3   177.2  1700.5   187.1 1703.49   190.2 1705.11   201.4 1714.13
#Mann= 4 ,-1 , 0
       0     .04       0   77.25      .1       0      99    .045       0
   108.6      .1       0
Bank Sta=99,108.6
XS Rating Curve= 0 ,0
Exp/Cntr(USF)=0,0
Exp/Cntr=0.3,0.1

Type RM Length L Ch R = 1 ,5036    ,111.3,98,83.8
XS GIS Cut Line= 4
2028781.54876551215110.0452142852028825.66554972215103.309622899
2028880.63391314215130.1347726192028938.87623616215114.269066025
#Sta/Elev= 30
       0 1674.33    17.4 1674.69    21.3 1674.28    24.7 1673.15      28 1671.13
    31.3 1668.32    37.9 1662.15    43.3 1658.23    44.6 1657.42    48.2 1655.99
    55.5 1653.56    66.5 1648.88    70.5 1647.89    73.8 1647.97      811649.224
    84.7 1649.23    88.4 1648.12    92.9 1647.37    95.7 1647.49    99.3 1648.48
     103 1650.78     110  1655.9   116.8 1658.64   120.2 1660.45   133.8 1669.73
   140.6 1673.98   150.2 1680.61   154.2 1682.79   157.6 1684.27   166.2 1687.45
#Mann= 4 ,-1 , 0
       0     .04       0    55.5      .1       0    66.5    .045       0
      81      .1       0
#XS Ineff= 2 , 0
                              95            1652
Permanent Ineff=
       F       F
Bank Sta=66.5,81
XS Rating Curve= 0 ,0
Exp/Cntr(USF)=0,0
Exp/Cntr=0.3,0.1

Type RM Length L Ch R = 1 ,4938    ,134.2,143.9,155.9
XS GIS Cut Line= 4
2028730.57413316215214.3342953552028782.90470284215235.266523229
2028852.31156369215220.9444725792028951.46422204215154.842700344
#Sta/Elev= 30
       0 1688.85      14 1680.11    24.6 1675.37    31.8  1673.4    45.8  1672.9
    56.4 1670.55    59.8  1669.4    66.5 1663.73    69.8 1661.86    91.9 1663.08
     100  1662.7   103.3 1662.02   106.7 1660.34     110 1657.98   127.2  1644.6
   134.6 1639.59   138.5  1637.6     142 1636.99   151.5 1636.45   159.2 1637.59
   162.2 1638.49   170.4 1642.74   185.8 1647.11   194.7 1651.18   205.5 1657.73
   212.4 1663.27   217.7 1666.88   225.3 1670.61   236.1 1678.72   246.4 1685.88
#Mann= 5 ,-1 , 0
       0      .1       0      10     .04       0      40      .1       0
   138.5    .045       0   159.2      .1       0
Bank Sta=138.5,159.2
XS Rating Curve= 0 ,0
Exp/Cntr(USF)=0,0
Exp/Cntr=0.3,0.1

Type RM Length L Ch R = 1 ,4794    ,110.4,99,89.6
XS GIS Cut Line= 4
2028846.52148042215332.3585995962028890.34752969  215328.5804919
2028934.04238431215340.7682063212028991.86821466215330.287274569
#Sta/Elev= 30
       0 1652.86     5.4 1652.33       9 1651.14    11.9 1649.45    18.5 1644.72
    25.1 1639.19    31.7 1634.42      35 1632.59    38.3  1631.6    41.6 1631.18
    48.3 1631.24    55.1 1630.76    65.3  1627.6    68.7 1626.93    72.1 1626.63
      79 1627.05    79.3 1627.77    81.4 1632.55    82.4 1634.48    85.8 1647.27
    86.8 1649.78    88.7 1655.24    89.2 1656.38    92.5 1661.66    99.2 1668.09
   102.5 1670.73   114.4 1678.63     122 1683.19   139.2 1692.27   148.1 1697.64
#Mann= 4 ,-1 , 0
       0     .04       0    65.3    .045       0    79.3     .04       0
   89.35      .1       0
Bank Sta=65.3,79.3
XS Rating Curve= 0 ,0
Exp/Cntr(USF)=0,0
Exp/Cntr=0.3,0.1