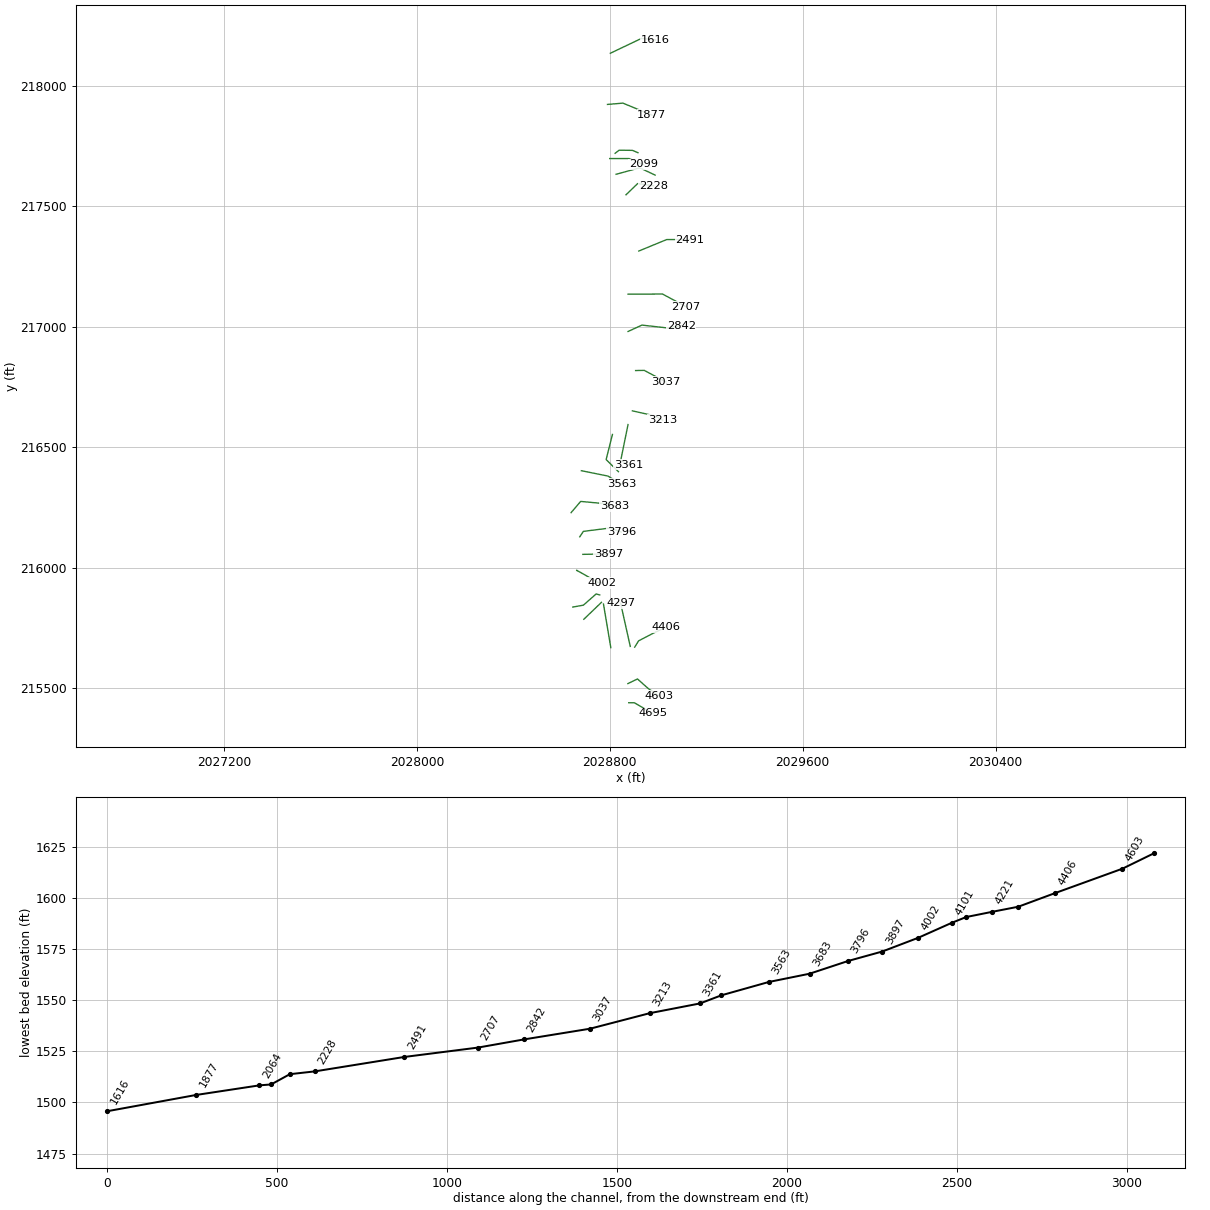
HEC-RAS study SPRUCERN.prj: SPRUCERN

--- SPRUCERN.g01 (geometry) --- (continued)

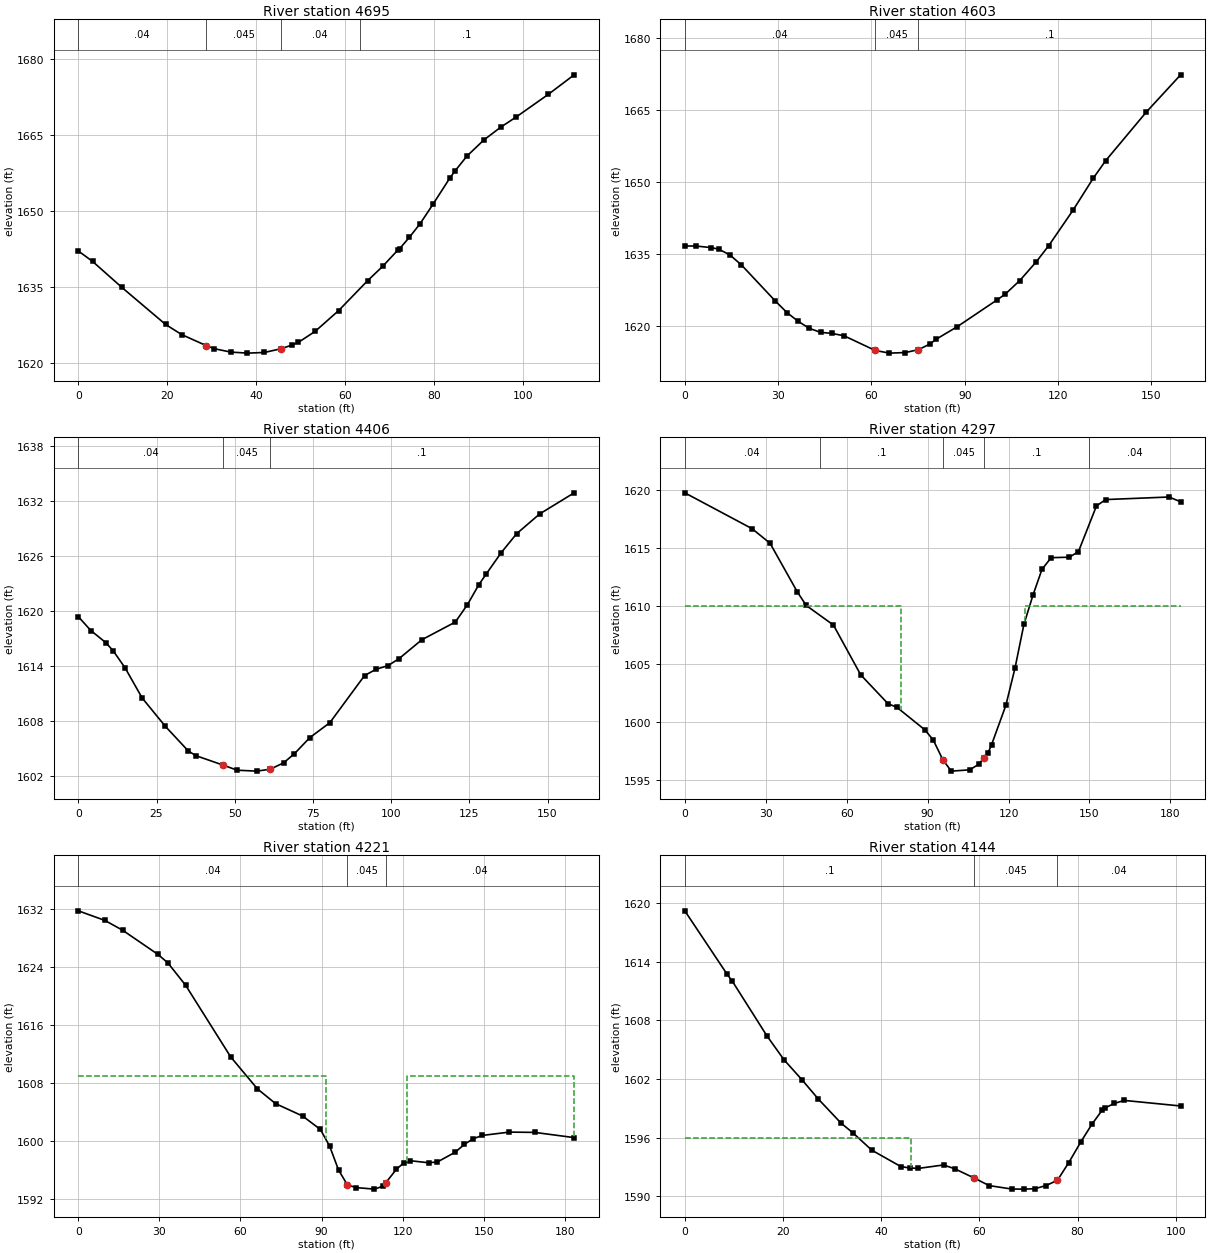
Type RM Length L Ch R = 1 ,4695    ,94.5,92,91
XS GIS Cut Line= 3
 2028878.1520223215440.7290648962028901.35374435215440.729064896
2028977.65171496215396.556555599
#Sta/Elev= 30
       0 1642.09     3.2 1640.03     9.8 1634.87    19.6 1627.56    23.2 1625.56
    28.7 1623.38    30.5 1622.77    34.2 1622.09      38 1621.88    41.8 1622.01
    45.5 1622.74    47.9 1623.45    49.4 1623.99    53.2 1626.18    58.5 1630.31
      65 1636.22    68.4 1639.07    71.9 1642.38    72.2 1642.56    74.4 1644.82
    76.8 1647.51    79.7 1651.36    83.5 1656.57    84.7    1658    87.3 1660.86
    91.1 1664.05    94.9 1666.59    98.4 1668.62   105.6 1673.09   111.4 1676.95
#Mann= 4 ,-1 , 0
       0     .04       0    28.7    .045       0    45.5     .04       0
    63.2      .1       0
Bank Sta=28.7,45.5
XS Rating Curve= 0 ,0
Exp/Cntr(USF)=0,0
Exp/Cntr=0.3,0.1

Type RM Length L Ch R = 1 ,4603    ,178.4,197.4,208.3
XS GIS Cut Line= 4
2028874.89633587215520.0549919422028914.55739921 215539.33467551
2028960.27779167215498.5719159652029005.44733603 215468.82611846
#Sta/Elev= 30
       0 1636.72     3.6 1636.71     8.4 1636.39    10.9 1636.06    14.5 1634.86
    18.2 1632.78    29.1 1625.26    32.9 1622.82    36.4 1621.06      40 1619.57
    43.7 1618.73    47.2 1618.53    51.2 1618.02    61.2 1614.97    65.8 1614.41
    70.9 1614.53    75.1 1615.13    78.8  1616.3    80.8  1617.3    87.6 1619.92
   100.5 1625.54     103 1626.68   107.7 1629.53     113 1633.43     117 1636.79
   124.8 1644.16   131.3 1650.82   135.3 1654.48   148.4 1664.63   159.4 1672.36
#Mann= 3 ,-1 , 0
       0     .04       0    61.2    .045       0    75.1      .1       0
Bank Sta=61.2,75.1
XS Rating Curve= 0 ,0
Exp/Cntr(USF)=0,0
Exp/Cntr=0.3,0.1

Type RM Length L Ch R = 1 ,4406    ,90.9,109.1,123.6
XS GIS Cut Line= 4
2028902.98634313  215671.48609462028919.13623882215697.359760857
2028978.45577904215728.2755744822029033.54058923215754.716283376
#Sta/Elev= 30
       0 1619.38       4 1617.87     8.8 1616.54    11.2 1615.63      15 1613.76
    20.4  1610.5    27.8 1607.41    35.1 1604.73    37.5 1604.21    46.31603.165
    50.8 1602.61      57 1602.51    61.31602.714    65.6 1603.41    69.1 1604.42
      74 1606.17    80.4  1607.8    91.5 1612.95    95.2 1613.64    98.9 1614.02
   102.5 1614.79   109.8 1616.86   120.5 1618.79   124.4  1620.7     128 1622.86
   130.3    1624   135.2 1626.38   140.1 1628.44   147.5 1630.61   158.5 1632.91
#Mann= 3 ,-1 , 0
       0     .04       0    46.3    .045       0    61.3      .1       0
Bank Sta=46.3,61.3
XS Rating Curve= 0 ,0
Exp/Cntr(USF)=0,0
Exp/Cntr=0.5,0.3

Type RM Length L Ch R = 1 ,4297    ,77,76.1,75.4
XS GIS Cut Line= 2
2028884.56902191215674.3547027342028844.53621016215853.758650673
#Sta/Elev= 30
       0 1619.74    24.9 1616.66    31.6  1615.4    41.7 1611.22      45 1610.05
    55.1 1608.36    65.2 1604.08    75.3  1601.6    78.7 1601.27      89 1599.34
    92.1 1598.47    95.71596.751    98.8 1595.79   105.6  1595.9   108.9 1596.37
     111 1596.95   112.3 1597.31   113.7 1598.05     119 1601.44   122.4 1604.65
   125.7 1608.41   129.1 1610.96   132.4 1613.15   135.8 1614.16   142.5  1614.2
   145.9 1614.67   152.6 1618.61     156 1619.16   179.5 1619.38   183.8 1618.97
#Mann= 5 ,-1 , 0
       0     .04       0      50      .1       0    95.7    .045       0
     111      .1       0     150     .04       0
#XS Ineff= 2 , 0
              80    1610     126            1610
Permanent Ineff=
       F       F
Bank Sta=95.7,111
XS Rating Curve= 0 ,0
Exp/Cntr(USF)=0,0
Exp/Cntr=0.5,0.3

Type RM Length L Ch R = 1 ,4221    ,90.6,77.2,68.2
XS GIS Cut Line= 2
2028803.85418322215669.301419004 2028773.4190483215850.302538088
#Sta/Elev= 30
       0 1631.73     9.8 1630.41    16.4 1629.05    29.4 1625.73    33.1 1624.56
    39.7 1621.46    56.4 1611.56    66.3 1607.15      73 1605.12      83 1603.41
    89.6 1601.55      93 1599.26    96.3 1595.96    99.6 1593.89   102.9 1593.53
   109.6 1593.32   112.9 1593.75   113.81594.205   117.7 1596.05   120.5 1596.97
   122.9 1597.24   129.6 1596.96   132.9 1597.07   139.5 1598.42   142.9 1599.51
   146.2 1600.28   149.5 1600.73   159.5 1601.19   168.9 1601.15   183.5 1600.43
#Mann= 3 ,-1 , 0
       0     .04       0    99.6    .045       0   113.8     .04       0
#XS Ineff= 2 , 0
            91.5  1608.9   121.5          1608.9
Permanent Ineff=
       F       F
Bank Sta=99.6,113.8
XS Rating Curve= 0 ,0
Exp/Cntr(USF)=0,0
Exp/Cntr=0.5,0.3

Type RM Length L Ch R = 1 ,4144    ,42.9,42.6,41.7
XS GIS Cut Line= 2
2028692.14375915215787.0886950622028765.03211626215857.061517886
#Sta/Elev= 30
       0 1619.19     8.6 1612.72     9.7 1611.98    16.7 1606.43    20.2 1603.97
    23.9  1601.9    27.2 1599.95    31.8  1597.5    34.2 1596.51    38.1 1594.72
      44 1593.05    45.8  1592.9    47.6 1592.86    52.7 1593.21      55 1592.82
      591591.861      62  1591.1    66.6 1590.75      69 1590.74    71.3 1590.78
    73.6 1591.11    75.9 1591.64    78.2 1593.44    80.7 1595.59    82.9 1597.35
      85  1598.8    85.5 1599.02    87.5  1599.5    89.5 1599.81     101 1599.24
#Mann= 3 ,-1 , 0
       0      .1       0      59    .045       0    75.9     .04       0
#XS Ineff= 2 , 0
              46    1596
Permanent Ineff=
       F       F
Bank Sta=59,75.9
XS Rating Curve= 0 ,0
Exp/Cntr(USF)=0,0
Exp/Cntr=0.3,0.1

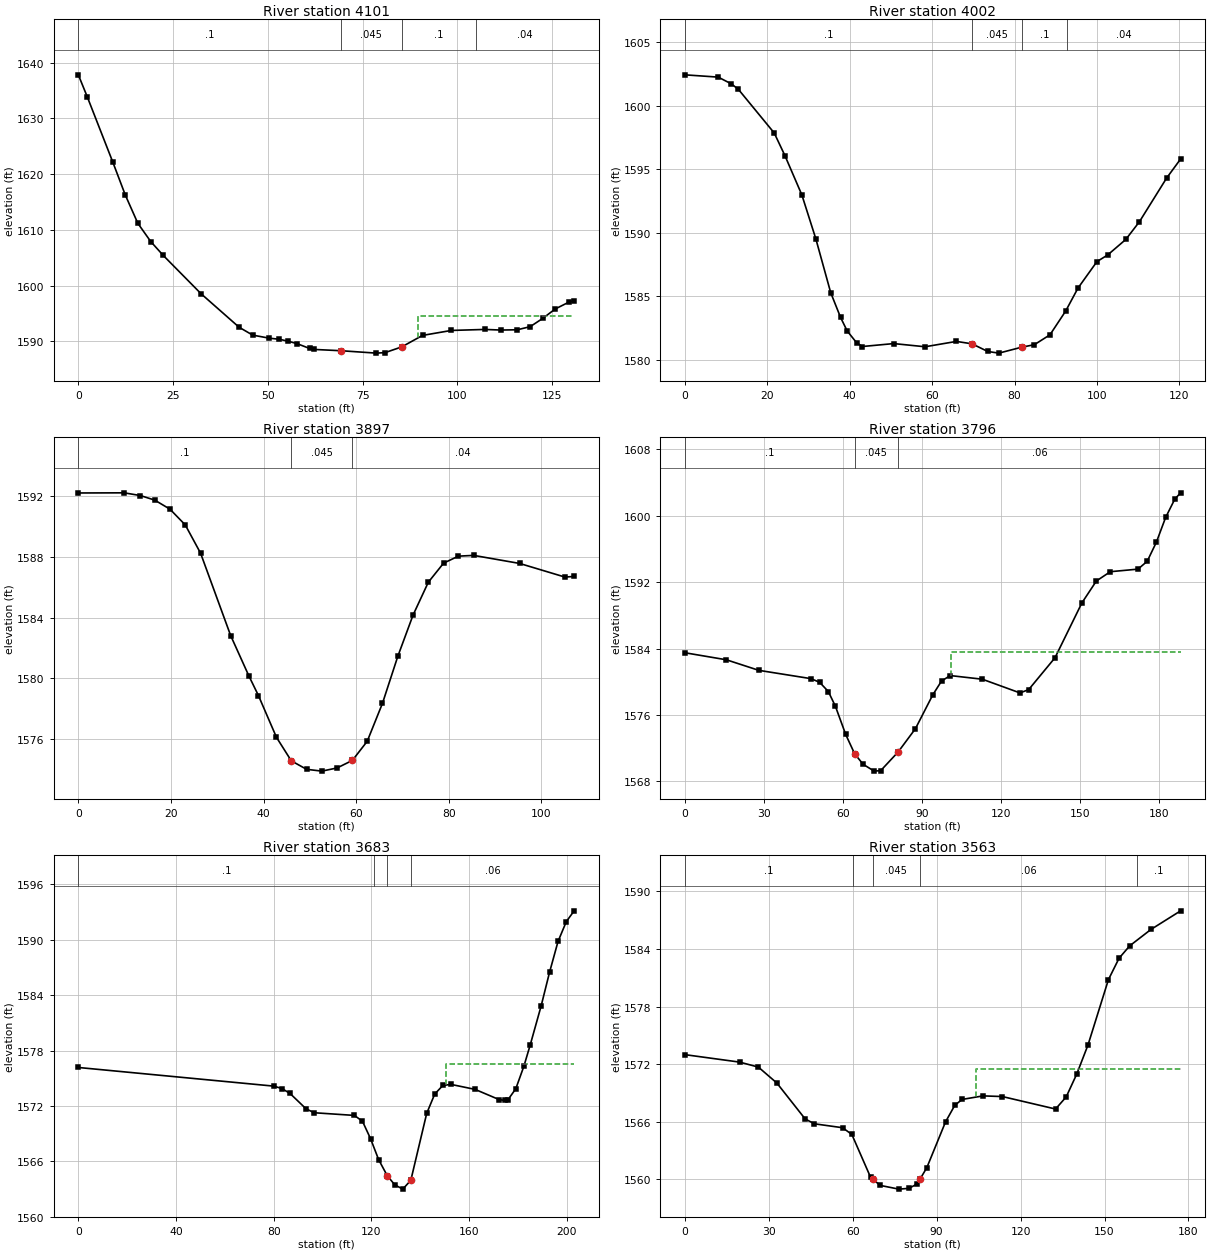
Type RM Length L Ch R = 1 ,4101    ,112.4,99,81.2
XS GIS Cut Line= 4
2028646.06847626215837.5189107392028690.19140923215845.451123408
2028743.23808144215892.0528728332028757.95643764215887.760422476
#Sta/Elev= 30
       0 1637.83     2.4 1633.81     9.1 1622.16    12.4 1616.25    15.7 1611.19
    19.1 1607.92    22.4 1605.43    32.4 1598.54    42.4 1592.55      46 1591.13
    50.4 1590.58      53 1590.39    55.4 1590.03    57.7  1589.6      61 1588.74
    62.3 1588.56    69.3 1588.33    78.6  1587.9    80.9 1587.99    85.3 1589.01
    90.8 1591.08    98.4 1591.97   107.2 1592.15   111.5 1592.04   115.8 1592.09
   119.2 1592.65   122.6 1594.17   125.8 1595.82   129.5 1597.08   130.8 1597.29
#Mann= 4 ,-1 , 0
       0      .1       0    69.3    .045       0    85.3      .1       0
  104.83     .04       0
#XS Ineff= 2 , 0
                           89.64         1594.53
Permanent Ineff=
       F       F
Bank Sta=69.3,85.3
XS Rating Curve= 0 ,0
Exp/Cntr(USF)=0,0
Exp/Cntr=0.3,0.1

Type RM Length L Ch R = 1 ,4002    ,99.3,105.3,111.4
XS GIS Cut Line= 5
 2028663.4880477 215989.327623592028661.76311731215990.324162377
2028688.59647044215975.4402611142028749.56861685215940.193483795
2028766.54368395215937.586621344
#Sta/Elev= 30
       0 1602.41     8.1 1602.23    11.3  1601.7      13 1601.27    21.7 1597.84
    24.3 1596.06    28.4 1592.98    31.8 1589.52    35.4  1585.3    37.8 1583.35
    39.4 1582.29    41.7 1581.36    43.1 1581.07    50.7  1581.3    58.3 1581.05
    65.9 1581.47    69.7 1581.28    73.5 1580.68    76.2 1580.55    81.81581.021
    84.8 1581.21    88.6 1581.99    92.4 1583.85    95.4 1585.66     100 1587.74
   102.6 1588.26     107 1589.48   110.3 1590.87   116.9  1594.3   120.3  1595.8
#Mann= 4 ,-1 , 0
       0      .1       0    69.7    .045       0    81.8      .1       0
   92.68     .04       0
Bank Sta=69.7,81.8
XS Rating Curve= 0 ,0
Exp/Cntr(USF)=0,0
Exp/Cntr=0.3,0.1

Type RM Length L Ch R = 1 ,3897    ,99.2,100.5,102
XS GIS Cut Line= 2
2028687.71259277216056.1505224072028794.79746379216058.133575574
#Sta/Elev= 27
       0 1592.23     9.9 1592.24    13.4 1592.06    16.5 1591.76    19.8 1591.16
    23.1 1590.12    26.4 1588.26    32.9 1582.82    36.8 1580.18    38.9 1578.86
    42.8  1576.1      46 1574.55    49.3 1573.99    52.6 1573.87    55.9 1574.08
    59.2 1574.58    62.4 1575.84    65.7 1578.35      69 1581.44    72.3 1584.17
    75.6 1586.34    78.9  1587.6    82.1 1588.06    85.4 1588.11    95.3 1587.58
   105.1 1586.68   107.1 1586.72
#Mann= 3 ,-1 , 0
       0      .1       0      46    .045       0    59.2     .04       0
Bank Sta=46,59.2
XS Rating Curve= 0 ,0
Exp/Cntr(USF)=0,0
Exp/Cntr=0.3,0.1

Type RM Length L Ch R = 1 ,3796    ,116.3,113.5,110.3
XS GIS Cut Line= 4
2028675.14215872216128.9926511552028690.16545787216151.587711518
2028801.27003761216165.5220741612028847.36656328216148.449286879
#Sta/Elev= 30
       0  1583.5    15.8 1582.65    28.1 1581.38    47.9 1580.38    51.2 1579.94
    54.5 1578.83    57.2 1577.05    61.1 1573.66    64.51571.331    67.7 1570.07
    71.9 1569.24    74.4  1569.3      81 1571.54    87.6 1574.36    94.2 1578.44
    97.5 1580.09   100.8 1580.75     113 1580.31   127.3 1578.66   130.6 1579.06
   140.6  1582.9   150.8  1589.5   156.3 1592.14   161.6 1593.26   172.1 1593.57
   175.6 1594.51   179.1 1596.82   182.6 1599.79   186.1 1602.01   188.3 1602.76
#Mann= 3 ,-1 , 0
       0      .1       0    64.5    .045       0      81     .06       0
#XS Ineff= 2 , 0
                          101.27         1583.58
Permanent Ineff=
       F       F
Bank Sta=64.5,81
XS Rating Curve= 0 ,0
Exp/Cntr(USF)=0,0
Exp/Cntr=0.3,0.1

Type RM Length L Ch R = 1 ,3683    ,120.9,119.7,117.8
XS GIS Cut Line= 4
2028639.12779017216229.1719112322028678.78885351216275.773660657
2028791.07155245216265.4087514462028818.75743026216256.321683726
#Sta/Elev= 30
       0 1576.17    80.1 1574.15    83.4 1573.89    86.7 1573.36    93.3 1571.69
    96.6 1571.27   113.1 1570.98   116.4 1570.34   119.7 1568.46     123  1566.2
   126.5 1564.47   129.6 1563.47   132.9    1563   136.2 1563.96   142.7  1571.2
     146  1573.3   149.3 1574.22   152.6 1574.34   162.5  1573.8   172.4 1572.69
   174.7 1572.61   175.8 1572.61   179.2 1573.87   182.5  1576.3   185.1 1578.61
   189.6 1582.86     193 1586.46   196.5 1589.82   199.9 1591.97   203.1 1593.13
#Mann= 4 ,-1 , 0
       0      .1       0  121.19     .06       0   126.5    .045       0
   136.2     .06       0
#XS Ineff= 2 , 0
                          150.58         1576.54
Permanent Ineff=
       F       F
Bank Sta=126.5,136.2
XS Rating Curve= 0 ,0
Exp/Cntr(USF)=0,0
Exp/Cntr=0.3,0.1

Type RM Length L Ch R = 1 ,3563    ,158.9,139.3,64.1
XS GIS Cut Line= 3
2028681.76343327 216403.184826642028791.31397313216381.096680332
2028847.84413601216348.155101255
#Sta/Elev= 30
       0 1572.99    19.6 1572.21    26.3 1571.69    32.9 1570.03      43 1566.29
    46.3 1565.78    56.4 1565.37    59.7 1564.67    66.4  1560.2    67.11560.035
    69.8 1559.36    76.5 1558.97    80.1 1559.05    83.1 1559.52      841559.978
    86.5 1561.21    93.2 1565.99    96.5 1567.71    99.1 1568.32   106.6 1568.69
   113.5 1568.62   132.5 1567.32   136.3 1568.58   140.1 1570.98   144.1    1574
   151.4 1580.81   155.2 1583.04     159 1584.33   166.6 1586.04   177.2 1587.98
#Mann= 5 ,-1 , 0
       0      .1       0      60     .06       0    67.1    .045       0
      84     .06       0  161.76      .1       0
#XS Ineff= 2 , 0
                          104.22         1571.47
Permanent Ineff=
       F       F
Bank Sta=67.1,84
XS Rating Curve= 0 ,0
Exp/Cntr(USF)=0,0
Exp/Cntr=0.5,0.3

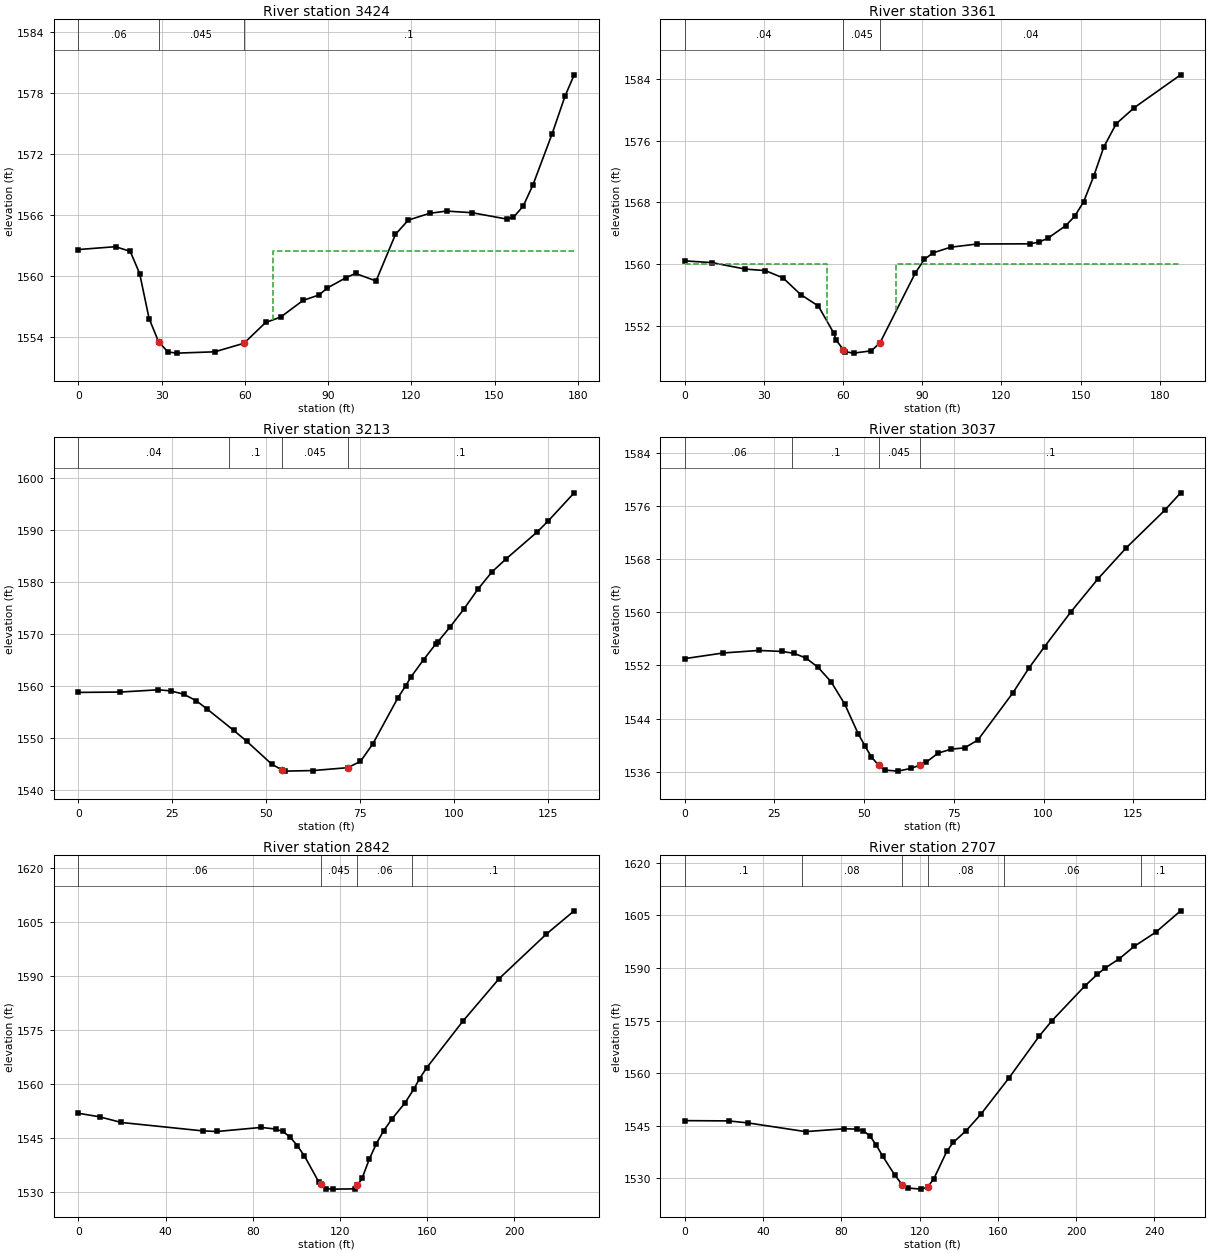
Type RM Length L Ch R = 1 ,3424    ,61.4,63.1,111.7
XS GIS Cut Line= 3
2028810.62079981 216553.41310137 2028784.5073347216449.386620995
 2028835.4021496216399.254078509
#Sta/Elev= 30
       0 1562.64    13.4 1562.92    18.7 1562.46    22.1 1560.28    25.5 1555.86
    28.9 1553.59    32.3 1552.57    35.6 1552.46    49.2 1552.59    59.7 1553.43
    67.5 1555.47    72.9    1556      81 1557.64    86.7 1558.17    89.8 1558.87
    96.5 1559.88    99.9 1560.29   107.3 1559.55   114.3 1564.13   118.9 1565.53
   126.6  1566.2   132.7 1566.42   141.9 1566.26   154.5 1565.63   156.8 1565.81
   160.3 1566.89   163.8 1568.96   170.7 1573.97   175.4 1577.71   178.7 1579.81
#Mann= 3 ,-1 , 0
       0     .06       0    28.9    .045       0    59.7      .1       0
#XS Ineff= 2 , 0
              18  1562.5      70          1562.5
Permanent Ineff=
       F       F
Bank Sta=28.9,59.7
XS Rating Curve= 0 ,0
Exp/Cntr(USF)=0,0
Exp/Cntr=0.5,0.3

Type RM Length L Ch R = 1 ,3361    ,132.7,147.9,170.8
XS GIS Cut Line= 3
2028875.29474663 216594.672636822028845.23453588216446.648516743
2028876.64897332216427.306144267
#Sta/Elev= 30
       0 1560.43    10.4  1560.2      23 1559.36    30.5 1559.17    37.2 1558.23
    43.9 1556.07    50.6 1554.58    56.4  1551.1    57.3 1550.18    60.11548.924
    60.6 1548.66      64 1548.47    70.7 1548.77      74 1549.82    87.4 1558.89
    90.8 1560.63    94.1 1561.47   100.7  1562.2   110.9 1562.62   130.9 1562.64
   134.3 1562.88   137.6 1563.37   144.3 1564.98   147.7 1566.19   151.1 1568.06
     155 1571.44   158.8 1575.21   163.5 1578.21   170.4 1580.31   187.9 1584.55
#Mann= 3 ,-1 , 0
       0     .04       0    60.1    .045       0      74     .04       0
#XS Ineff= 2 , 0
              54    1560      80            1560
Permanent Ineff=
       F       F
Bank Sta=60.1,74
XS Rating Curve= 0 ,0
Exp/Cntr(USF)=0,0
Exp/Cntr=0.5,0.3

Type RM Length L Ch R = 1 ,3213    ,178.2,175.7,173.2
XS GIS Cut Line= 3
2028893.44116689216651.4387341812028986.78663136216630.522435662
2029018.76609604216613.236238539
#Sta/Elev= 30
       0 1558.81    11.2 1558.88    21.3 1559.31    24.6  1559.1      28 1558.48
    31.4 1557.21    34.3 1555.61    41.4  1551.5    44.8 1549.45    51.5 1545.03
    54.2 1543.94    54.9  1543.7    62.5 1543.81    71.7 1544.36    75.1 1545.56
    78.4 1548.93    85.1  1557.8    87.2 1560.13    88.5 1561.72    91.9 1565.08
    95.2 1568.14    95.7 1568.51    98.9 1571.31   102.6 1574.77   106.4 1578.64
   110.1 1581.93   113.8 1584.39   122.1 1589.57     125 1591.65     132 1597.12
#Mann= 4 ,-1 , 0
       0     .04       0      40      .1       0    54.2    .045       0
    71.7      .1       0
Bank Sta=54.2,71.7
XS Rating Curve= 0 ,0
Exp/Cntr(USF)=0,0
Exp/Cntr=0.3,0.1

Type RM Length L Ch R = 1 ,3037    ,191.2,194.7,199.4
XS GIS Cut Line= 3
 2028906.7343751216818.7224928672028942.74179684  216819.3079794
2029032.90672281 216771.29808375
#Sta/Elev= 30
       0 1553.03    10.7 1553.88    20.6 1554.26    27.1 1554.11    30.4 1553.83
    33.7 1553.14    37.1 1551.75    40.8 1549.52    44.6 1546.16    48.3 1541.76
    50.3 1539.81      52 1538.23      54 1537.01    55.7 1536.26    59.4  1536.1
    63.1 1536.52    65.6 1537.02    67.3 1537.45    70.6 1538.81    74.3 1539.41
      78  1539.6    81.7 1540.79    91.5 1547.92    95.9  1551.6   100.3 1554.85
   107.7 1560.12   115.2 1565.06     123 1569.68   133.8 1575.37   138.2 1577.98
#Mann= 4 ,-1 , 0
       0     .06       0      30      .1       0      54    .045       0
    65.6      .1       0
Bank Sta=54,65.6
XS Rating Curve= 0 ,0
Exp/Cntr(USF)=0,0
Exp/Cntr=0.3,0.1

Type RM Length L Ch R = 1 ,2842    ,133.8,135.3,136.7
XS GIS Cut Line= 4
2028875.58129582216980.7401735382028933.00853279217007.186927405
2029040.32878748216995.1978053622029095.65597084217005.013918539
#Sta/Elev= 30
       0 1551.89     9.8 1550.89    19.7 1549.33      57    1547    63.6 1546.83
    83.9 1547.96    90.5  1547.5    93.8 1546.83    97.1 1545.29   100.4 1542.93
   103.7 1540.05   110.3  1532.8   111.1 1532.38   113.6 1530.99   116.9 1530.85
   126.8 1530.92     128  1531.9   130.1  1533.8   133.4 1539.09   136.7 1543.49
     140 1546.99   143.7 1550.21   149.9 1554.82     154 1558.71   156.5 1561.51
   159.8 1564.52   176.4 1577.44     193 1589.22   214.7 1601.59   227.4 1608.01
#Mann= 4 ,-1 , 0
       0     .06       0   111.1    .045       0     128     .06       0
  153.22      .1       0
Bank Sta=111.1,128
XS Rating Curve= 0 ,0
Exp/Cntr(USF)=0,0
Exp/Cntr=0.3,0.1

Type RM Length L Ch R = 1 ,2707    ,209.8,216.3,221
XS GIS Cut Line= 3
2028875.43604512217135.3896556432029018.40482289217136.069715028
2029115.65331497217083.705142373
#Sta/Elev= 30
       0 1546.42    22.4 1546.34    32.3 1545.77    61.7 1543.28    81.4 1544.09
      88    1544    91.2  1543.5    94.5 1542.11    97.8 1539.48   101.1  1536.3
   107.4  1530.8   111.2 1528.07   114.2 1527.17   120.8 1526.86   124.1 1527.42
   127.3 1529.85   133.9 1537.65   137.2  1540.2   143.9  1543.6   151.3 1548.24
   165.7 1558.62   181.1 1570.52   187.5 1574.87   204.4 1584.84   210.9 1588.23
   214.6  1589.9   222.1 1592.66   229.6 1596.15   240.8 1600.26   253.4 1606.33
#Mann= 6 ,-1 , 0
       0      .1       0      60     .08       0   111.2    .045       0
   124.1     .08       0  162.97     .06       0  232.97      .1       0
Bank Sta=111.2,124.1
XS Rating Curve= 0 ,0
Exp/Cntr(USF)=0,0
Exp/Cntr=0.3,0.1

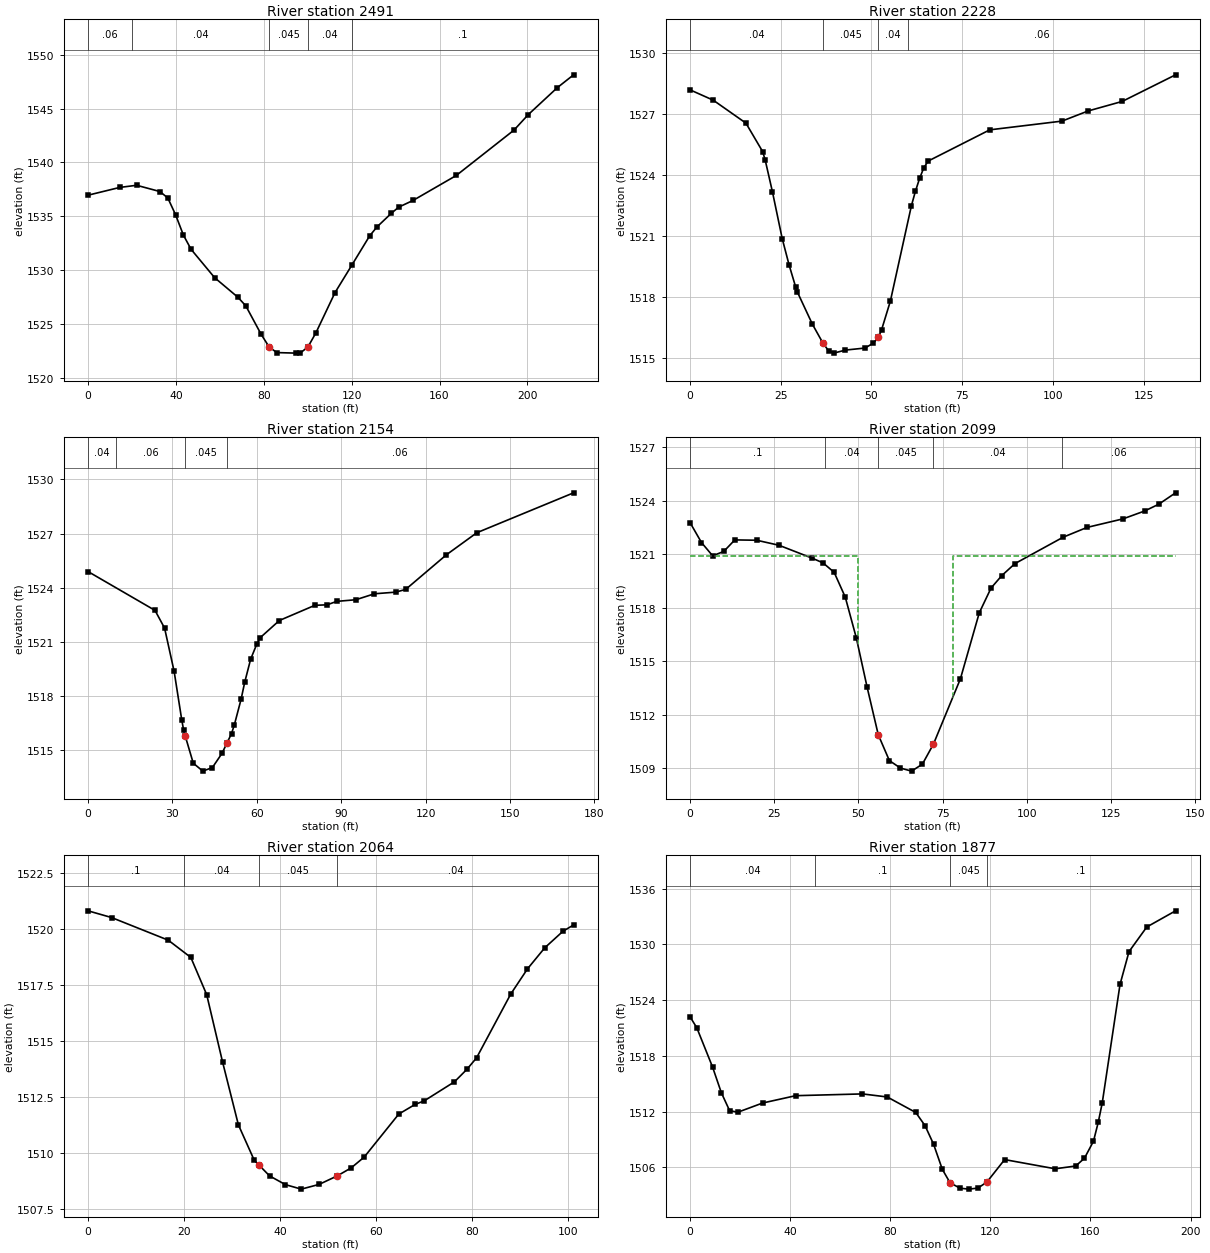
Type RM Length L Ch R = 1 ,2491    ,256.5,262.9,266.4
XS GIS Cut Line= 3
2028920.02034306217314.4235216982029035.63043853217362.027678658
2029131.59437399217362.027678658
#Sta/Elev= 30
       0 1536.95    14.4 1537.67    22.1 1537.87    32.7 1537.29    36.3 1536.69
    39.8 1535.15    43.4 1533.24    46.9 1531.92    57.6 1529.29    68.2 1527.47
    71.8 1526.67    78.8 1524.02    82.4 1522.86    85.9 1522.33    94.8 1522.28
    96.6 1522.29   100.1 1522.86   103.7 1524.16   112.4  1527.9     120 1530.43
   128.2 1533.18   131.5    1534   138.1 1535.28   141.4 1535.84     148 1536.47
   167.6 1538.78   193.9    1543   200.4 1544.44   213.6 1546.94     221 1548.13
#Mann= 5 ,-1 , 0
       0     .06       0      20     .04       0    82.4    .045       0
   100.1     .04       0     120      .1       0
Bank Sta=82.4,100.1
XS Rating Curve= 0 ,0
Exp/Cntr(USF)=0,0
Exp/Cntr=0.3,0.1

Type RM Length L Ch R = 1 ,2228    ,80.2,74,67.6
XS GIS Cut Line= 3
2028866.98713851217547.7644500312028915.42319959 217594.47220071
2028981.23175204217584.950963335
#Sta/Elev= 30
       0  1528.2     6.4 1527.69    15.4 1526.56      20 1525.16    20.7 1524.75
    22.7 1523.18    25.4 1520.87    27.3 1519.57    29.1 1518.49    29.6 1518.23
    33.7 1516.66    36.6 1515.73    38.2 1515.34    39.6 1515.23    42.8 1515.38
    48.2 1515.48    50.5 1515.72    51.9 1516.01    52.8 1516.39    55.2 1517.79
      61 1522.49    62.1  1523.2    63.3 1523.86    64.4 1524.35    65.6 1524.69
    82.6 1526.23   102.5 1526.66   109.7 1527.16   119.1 1527.63   133.8 1528.94
#Mann= 4 ,-1 , 0
       0     .04       0    36.6    .045       0    51.9     .04       0
      60     .06       0
Bank Sta=36.6,51.9
XS Rating Curve= 0 ,0
Exp/Cntr(USF)=0,0
Exp/Cntr=0.5,0.3

Type RM Length L Ch R = 1 ,2154    ,57.9,55.1,51.2
XS GIS Cut Line= 3
2028825.65395055217632.7345170792028923.84361526217659.602989059
2028987.86656756217629.304061012
#Sta/Elev= 30
       0  1524.9    23.8 1522.75    27.2 1521.77    30.6 1519.37    33.3 1516.69
      34  1516.1    34.51515.818    37.4 1514.29    40.8 1513.85    44.2 1514.05
    47.6 1514.83    49.3 1515.38      51 1515.93      52 1516.41    54.4 1517.83
    55.7 1518.78    57.8 1520.05      60 1520.89    61.2 1521.24      68 1522.19
    80.6 1523.03      85 1523.06    88.4 1523.25    95.2 1523.34   101.8 1523.67
   109.3 1523.76   112.9 1523.91   127.4 1525.83   138.2 1527.05   172.6 1529.26
#Mann= 4 ,-1 , 0
       0     .04       0      10     .06       0    34.5    .045       0
    49.3     .06       0
#XS Ineff= 2 , 0
            19.5  1521.5      64          1521.5
Permanent Ineff=
       F       F
Bank Sta=34.5,49.3
XS Rating Curve= 0 ,0
Exp/Cntr(USF)=0,0
Exp/Cntr=0.5,0.3

Type RM Length L Ch R = 1 ,2099    ,34.7,34.6,34.3
XS GIS Cut Line= 3
2028799.22280685217698.0694542322028879.61983657217698.093500252
2028938.42747918217673.450297633
#Sta/Elev= 30
       0 1522.77     3.4 1521.65     6.7 1520.91      10 1521.15    13.3  1521.8
    19.8 1521.78    26.4  1521.5    36.2 1520.78    39.5 1520.51    42.8 1519.98
    46.1 1518.59    49.4 1516.29    52.6 1513.53    55.9 1510.87    59.2 1509.42
    62.5    1509    65.8 1508.83      69 1509.22    72.3 1510.35    80.3 1514.01
    85.9 1517.71    89.4  1519.1    92.6  1519.8    96.5 1520.47   110.8 1521.95
   117.9  1522.5   128.6 1522.98     135 1523.42   139.2  1523.8   144.2 1524.44
#Mann= 5 ,-1 , 0
       0      .1       0      40     .04       0    55.9    .045       0
    72.3     .04       0   110.4     .06       0
#XS Ineff= 2 , 0
              50  1520.9      78          1520.9
Permanent Ineff=
       F       F
Bank Sta=55.9,72.3
XS Rating Curve= 0 ,0
Exp/Cntr(USF)=0,0
Exp/Cntr=0.5,0.3

Type RM Length L Ch R = 1 ,2064    ,190.8,186.9,181
XS GIS Cut Line= 4
2028821.69936012217719.7599720912028838.39882036217732.671925887
2028893.60284242217731.9603171252028916.47598121217722.302769635
#Sta/Elev= 27
       0  1520.8     4.9  1520.5    16.7 1519.49    21.4 1518.72    24.7 1517.06
      28 1514.06    31.3 1511.25    34.6 1509.67    35.61509.451    37.8 1508.97
    41.1 1508.58    44.4 1508.38    48.1 1508.59    51.91508.972    54.8 1509.33
    57.5 1509.81    64.7 1511.73    68.1 1512.16      70 1512.32    76.3 1513.17
    78.9 1513.73    80.9 1514.24      88 1517.08    91.5 1518.21    95.1 1519.15
    98.9 1519.89   101.1 1520.17
#Mann= 4 ,-1 , 0
       0      .1       0      20     .04       0    35.6    .045       0
    51.9     .04       0
Bank Sta=35.6,51.9
XS Rating Curve= 0 ,0
Exp/Cntr(USF)=0,0
Exp/Cntr=0.3,0.1

Type RM Length L Ch R = 1 ,1877    ,250.4,260.8,273.1
XS GIS Cut Line= 3
2028790.14001789217922.5395865752028854.09348252217927.992982785
2028974.06819913217878.416653608
#Sta/Elev= 30
       0 1522.21     2.7 1521.03       9  1516.8    12.5 1514.04    15.8 1512.11
    19.1 1511.94      29 1512.93    42.2 1513.72    68.9 1513.91    78.8 1513.58
    90.2 1511.91    93.9 1510.49    97.3  1508.5   100.8 1505.79   103.9 1504.34
   107.9 1503.76   111.4 1503.66     115 1503.77   118.6 1504.42   125.7 1506.84
   145.9 1505.85   154.1 1506.15   157.6 1506.99   161.2 1508.82   163.1 1510.85
   164.7 1512.94   171.8 1525.69   175.4 1529.23   182.5 1531.88     194 1533.62
#Mann= 4 ,-1 , 0
       0     .04       0      50      .1       0   103.9    .045       0
   118.6      .1       0
Bank Sta=103.9,118.6
XS Rating Curve= 0 ,0
Exp/Cntr(USF)=0,0
Exp/Cntr=0.3,0.1

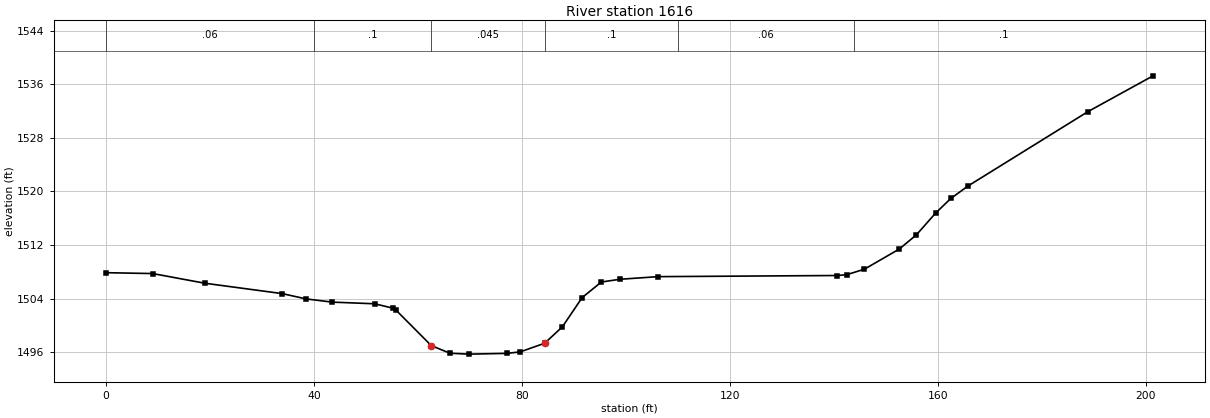
Type RM Length L Ch R = 1 ,1616    ,161.7,165.2,169.9
XS GIS Cut Line= 3
2028801.93564792218134.8398453672028931.82699048218196.725249415
2028988.95197883218189.924655563
#Sta/Elev= 30
       0 1507.87       9 1507.74      19  1506.3    33.9 1504.75    38.5 1503.96
    43.5 1503.48    51.7 1503.23    55.3 1502.56    55.8 1502.28    62.6 1496.98
    66.2 1495.85    69.8 1495.72    77.1 1495.83    79.7 1496.06    84.4 1497.35
    87.8  1499.8    91.6 1504.16    95.3 1506.48    98.9 1506.89   106.2 1507.28
   140.7 1507.45   142.5 1507.57   145.9  1508.4   152.6  1511.4   155.9 1513.53
   159.6 1516.78   162.5 1518.94   165.8  1520.8   188.9 1531.91   201.4 1537.24
#Mann= 6 ,-1 , 0
       0     .06       0      40      .1       0    62.6    .045       0
    84.4      .1       0     110     .06       0  143.88      .1       0
Bank Sta=62.6,84.4
XS Rating Curve= 0 ,0
Exp/Cntr(USF)=0,0
Exp/Cntr=0.3,0.1