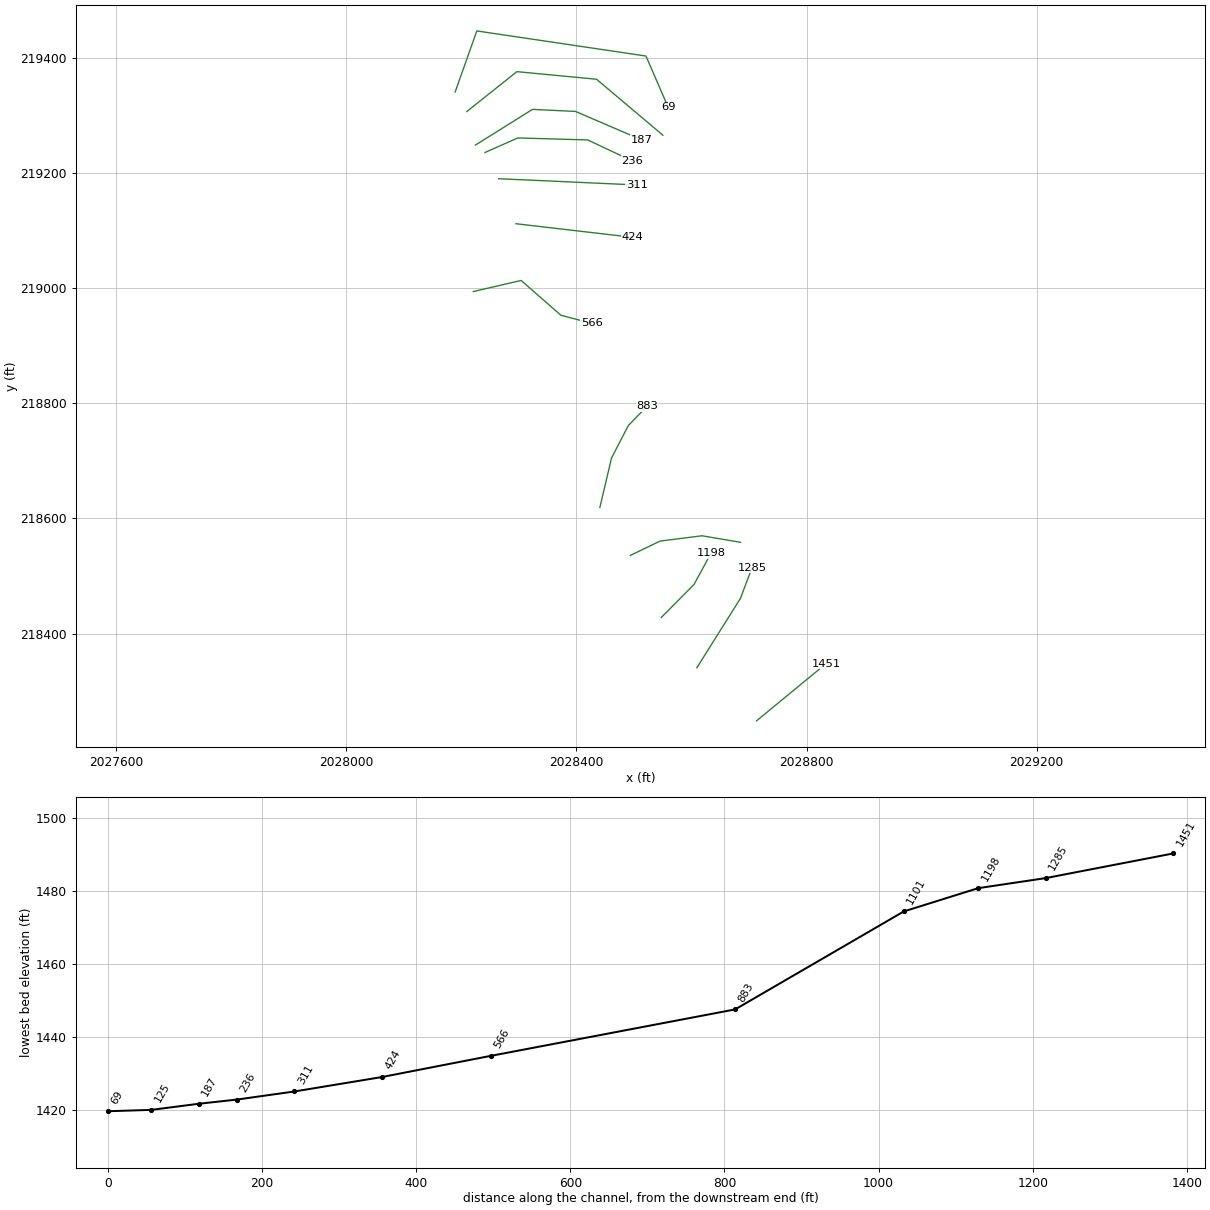
HEC-RAS study SPRUCERN.prj: SPRUCERN

--- SPRUCERN.g01 (geometry) --- (continued)

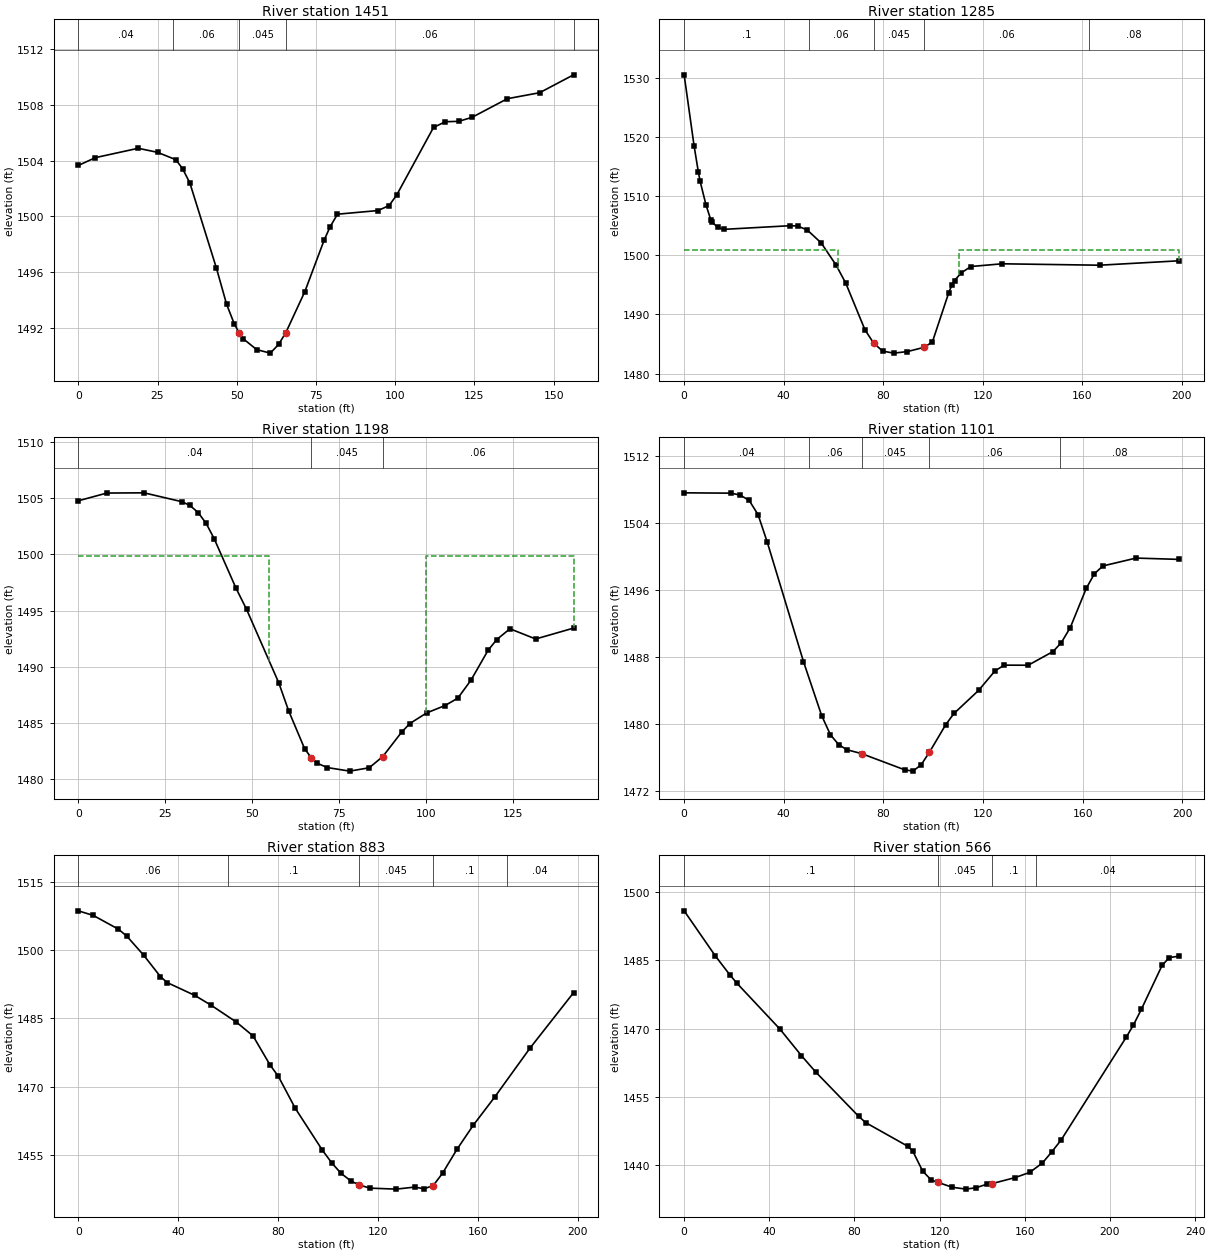
Type RM Length L Ch R = 1 ,1451    ,160.7,165.8,170.6
XS GIS Cut Line= 2
2028713.20704479218248.3721212182028833.90107151218347.670388658
#Sta/Elev= 30
       0 1503.65     5.4 1504.21    18.9 1504.88      25 1504.59    30.8 1504.06
    32.9 1503.42    35.2  1502.4    43.6 1496.29    46.8 1493.71    49.2 1492.32
    50.8 1491.64    52.1 1491.23    56.3 1490.46    60.6 1490.21    63.2 1490.83
    65.5 1491.68    71.5 1494.62    77.6 1498.31    79.5 1499.27    81.8 1500.16
    94.6 1500.42    98.1 1500.78   100.5 1501.54   112.1 1506.37   115.8 1506.78
   120.1 1506.81   124.3  1507.1   135.4 1508.43   145.6 1508.86   156.3 1510.14
#Mann= 5 ,-1 , 0
       0     .04       0      30     .06       0    50.8    .045       0
    65.5     .06       0  156.29     .04       0
Bank Sta=50.8,65.5
XS Rating Curve= 0 ,0
Exp/Cntr(USF)=0,0
Exp/Cntr=0.5,0.3

Type RM Length L Ch R = 1 ,1285    ,90.8,87.5,87.5
XS GIS Cut Line= 3
2028609.32272795218340.4645570032028685.16926613218461.302205389
2028705.07915158218514.155285295
#Sta/Elev= 30
       0 1530.49       4 1518.48     5.7  1514.1     6.4 1512.54     8.8 1508.48
    10.7    1506    11.2 1505.62    13.5  1504.7    15.9 1504.37    42.7 1504.99
    45.6 1504.94    49.5 1504.26    55.1 1502.08    61.1 1498.32      65 1495.25
    72.7 1487.38    76.21485.137    79.8 1483.79    84.3 1483.45    89.7 1483.71
    96.5 1484.43    99.8 1485.34   106.4 1493.69   107.6 1494.92   108.7 1495.72
   111.4 1497.02   115.3 1498.09   127.8 1498.55     167 1498.31   199.1 1499.06
#Mann= 5 ,-1 , 0
       0      .1       0      50     .06       0    76.2    .045       0
    96.5     .06       0  162.67     .08       0
#XS Ineff= 2 , 0
              62  1500.9   110.5          1500.9
Permanent Ineff=
       F       F
Bank Sta=76.2,96.5
XS Rating Curve= 0 ,0
Exp/Cntr(USF)=0,0
Exp/Cntr=0.5,0.3

Type RM Length L Ch R = 1 ,1198    ,103.7,96.5,81.5
XS GIS Cut Line= 3
2028547.55517187218427.9517750222028604.36206954218485.262681127
2028633.98663735218539.554292951
#Sta/Elev= 30
       0 1504.78     8.2 1505.47    18.9 1505.49    29.8  1504.7    32.1 1504.37
    34.5 1503.73    36.8 1502.76    39.1  1501.4    45.4 1496.98    48.4 1495.12
    57.7 1488.55    60.5 1486.09    65.1 1482.71      671481.901    68.7 1481.41
    71.6 1481.02    78.1  1480.7    83.7    1481    87.61481.995      93 1484.16
    95.4 1484.94   100.2 1485.88   105.5 1486.54   109.2  1487.2     113 1488.81
   117.9 1491.46   120.4 1492.42   124.2 1493.38   131.6 1492.47   142.5 1493.44
#Mann= 3 ,-1 , 0
       0     .04       0      67    .045       0    87.6     .06       0
#XS Ineff= 2 , 0
              55  1499.9     100          1499.9
Permanent Ineff=
       F       F
Bank Sta=67,87.6
XS Rating Curve= 0 ,0
Exp/Cntr(USF)=0,0
Exp/Cntr=0.5,0.3

Type RM Length L Ch R = 1 ,1101    ,201.7,218.8,236.3
XS GIS Cut Line= 4
2028493.72078815218535.7972257832028545.34533016218560.653964571
2028618.16553442218569.9437848672028685.29197786218558.556263213
#Sta/Elev= 30
       0  1507.6    18.8 1507.56    22.4 1507.34    26.1  1506.7    29.7 1504.97
    33.4 1501.67    47.9 1487.43    55.2 1480.97    58.7 1478.69      62 1477.51
    65.3 1476.89    71.21476.428    88.5 1474.49    91.8 1474.33    95.1 1475.07
    98.4 1476.56     105 1479.88   108.3 1481.22   118.2 1483.98   124.8 1486.32
   128.5    1487   138.1 1486.99   148.1 1488.63   151.4 1489.69     155 1491.49
   161.4 1496.17   164.7 1497.93   168.1 1498.86   181.4  1499.8   198.8 1499.64
#Mann= 5 ,-1 , 0
       0     .04       0      50     .06       0    71.2    .045       0
    98.4     .06       0  150.71     .08       0
Bank Sta=71.2,98.4
XS Rating Curve= 0 ,0
Exp/Cntr(USF)=0,0
Exp/Cntr=0.3,0.1

Type RM Length L Ch R = 1 ,883     ,345.4,317,278.3
XS GIS Cut Line= 4
2028440.78669075218619.3204418872028460.98445448218705.007924414
2028490.26840829218761.5542038212028522.77769108218795.099292376
#Sta/Elev= 30
       0 1508.62       6 1507.61    16.1 1504.58    19.5 1503.02    26.2 1498.87
    32.9 1494.18    35.6 1492.87    46.6 1490.07    53.2  1487.9    63.3  1484.2
      70 1481.16    76.8 1474.79    80.1 1472.32    86.9 1465.28    97.8 1456.05
   101.5 1453.31   105.2 1451.01   109.4 1449.23   112.6 1448.45   116.7 1447.74
   127.4 1447.52   134.8 1447.97   138.5 1447.59   142.2 1448.31   145.9    1451
   151.7 1456.26   158.2 1461.53   166.9  1467.8     181 1478.51   198.4 1490.65
#Mann= 5 ,-1 , 0
       0     .06       0      60      .1       0   112.6    .045       0
   142.2      .1       0  171.71     .04       0
Bank Sta=112.6,142.2
XS Rating Curve= 0 ,0
Exp/Cntr(USF)=0,0
Exp/Cntr=0.3,0.1

Type RM Length L Ch R = 1 ,566     ,132.9,141.6,149.6
XS GIS Cut Line= 4
2028220.75598805218994.4021361652028303.87435735219013.712464385
2028373.10389528218953.161476577   2028426.58809218939.197622782
#Sta/Elev= 30
       0 1495.89    14.7 1485.96    21.4 1481.88    24.8 1479.99      45 1469.93
    55.1  1464.1    61.8 1460.51      82 1450.77    85.3  1449.4     105 1444.23
   107.3 1443.23     112 1438.78     116 1436.84     119 1436.33   125.9 1435.22
   132.4 1434.81   137.3 1435.14   142.2  1435.9   144.5 1436.01   155.2 1437.31
   162.3 1438.48   168.3 1440.56   172.6 1442.95     177 1445.55   207.6 1468.13
     211 1470.82   214.7 1474.24   224.5 1483.94   227.9 1485.64   232.6 1485.94
#Mann= 4 ,-1 , 0
       0      .1       0     119    .045       0   144.5      .1       0
  165.33     .04       0
Bank Sta=119,144.5
XS Rating Curve= 0 ,0
Exp/Cntr(USF)=0,0
Exp/Cntr=0.3,0.1

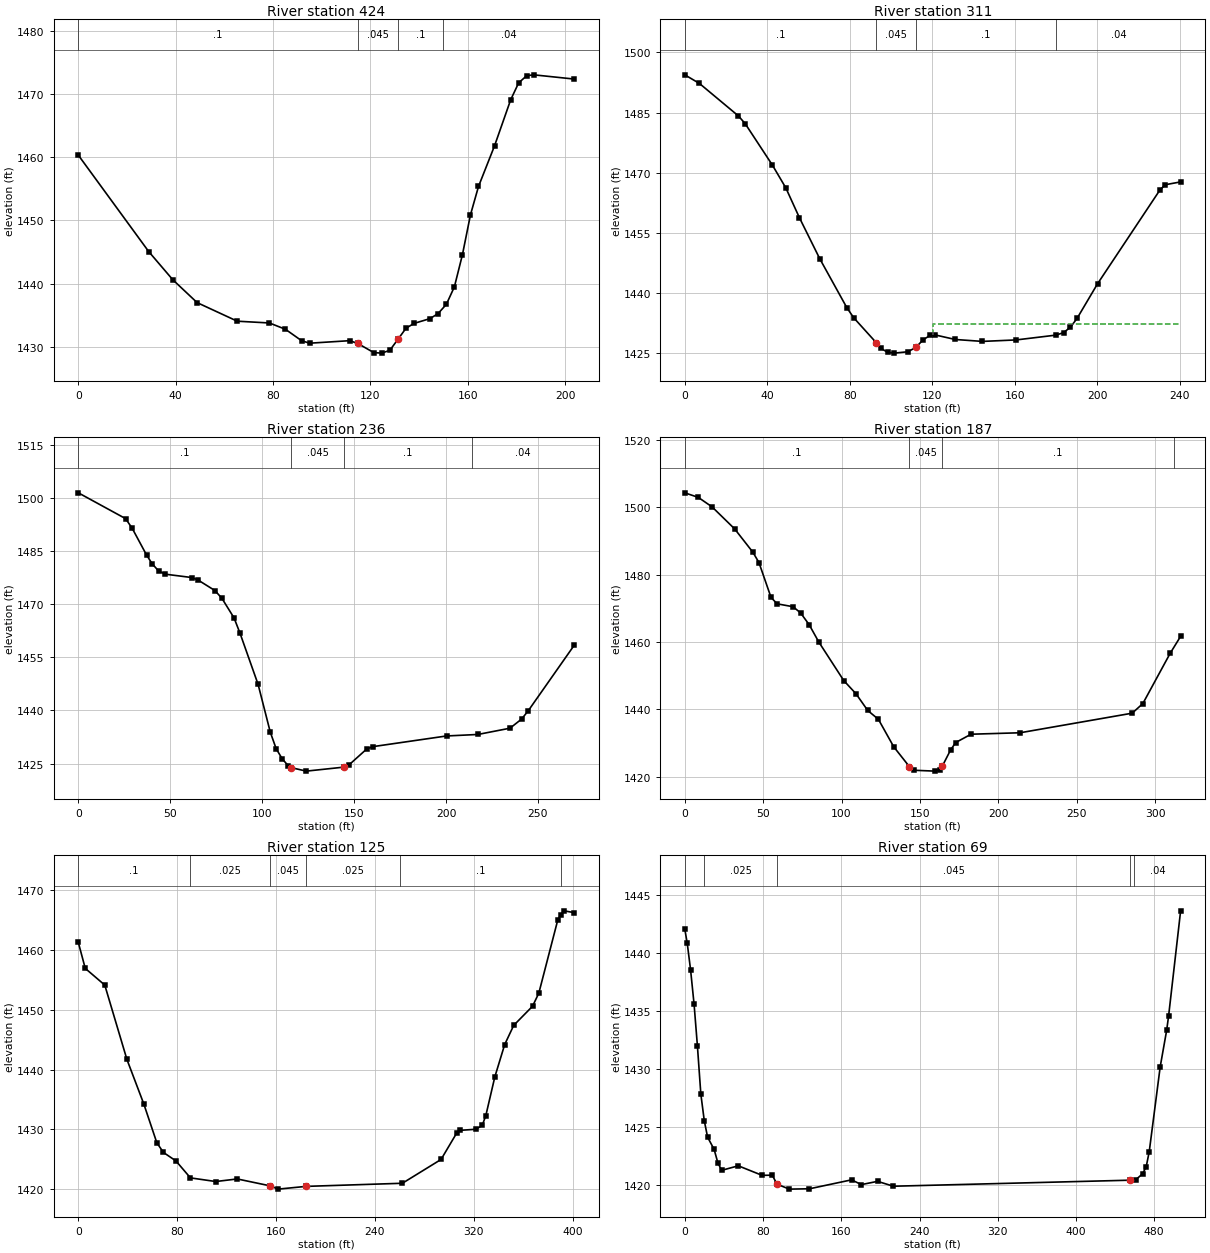
Type RM Length L Ch R = 1 ,424     ,109.5,113,109.7
XS GIS Cut Line= 2
2028294.89604597219112.3260497422028497.26372057219088.729818908
#Sta/Elev= 30
       0 1460.31    28.9 1445.07    38.8 1440.61    48.8 1436.99    65.3 1434.05
    78.5 1433.77    85.1 1432.77    91.7 1430.97      95 1430.57   111.5 1430.97
   114.8 1430.53   121.4 1429.08   124.7    1429     128 1429.46   131.3 1431.18
   134.6 1432.93   137.9  1433.7   144.5 1434.46   147.8 1435.26   151.2 1436.72
   154.5 1439.49   157.8 1444.57   161.1 1450.88   164.4 1455.36     171  1461.8
   177.6 1469.05   180.9 1471.75   184.2 1472.88   187.1 1473.02   203.7 1472.35
#Mann= 4 ,-1 , 0
       0      .1       0   114.8    .045       0   131.3      .1       0
     150     .04       0
Bank Sta=114.8,131.3
XS Rating Curve= 0 ,0
Exp/Cntr(USF)=0,0
Exp/Cntr=0.3,0.1

Type RM Length L Ch R = 1 ,311     ,74,74.4,74
XS GIS Cut Line= 2
 2028264.8214097219190.5402465152028505.00578929219179.716400952
#Sta/Elev= 30
       0 1494.39     7.1 1492.24      26 1484.15    29.3 1482.21    42.5 1471.88
      49 1466.21    55.6 1458.77    65.4 1448.62    78.6 1436.36    81.9 1433.88
    92.81427.686      95  1426.3    98.3 1425.28   101.6 1425.07   108.1 1425.41
     1121426.473   115.5 1428.37     119 1429.51   121.3 1429.61   131.1 1428.47
   144.3 1427.99   160.7 1428.36     180 1429.56   183.7 1430.19     187 1431.55
   190.2 1433.73   200.1 1442.33   230.2 1465.58   232.9 1467.01   240.4 1467.72
#Mann= 4 ,-1 , 0
       0      .1       0    92.8    .045       0     112      .1       0
     180     .04       0
#XS Ineff= 2 , 0
                          120.52         1432.28
Permanent Ineff=
       F       F
Bank Sta=92.8,112
XS Rating Curve= 0 ,0
Exp/Cntr(USF)=0,0
Exp/Cntr=0.3,0.1

Type RM Length L Ch R = 1 ,236     ,50.2,49.9,50.6
XS GIS Cut Line= 4
2028241.06502288219236.1347201712028298.07780144219261.418648051
2028419.60595761219257.9718785542028497.18292314219221.378970284
#Sta/Elev= 30
       0 1501.37    25.7 1494.09    29.3 1491.36    37.1 1483.84    40.1  1481.4
    43.7  1479.3    47.3 1478.42    61.6 1477.48      65 1476.81    74.3  1473.8
    78.1 1471.61    84.7 1466.08    87.9 1461.83    97.8  1447.3   104.4 1433.87
   107.6 1429.19   110.9 1426.33   114.2 1424.36   115.9 1423.83     124 1422.86
   144.5 1423.99     147 1424.51   156.9 1429.12   160.1 1429.76   200.3 1432.78
   217.3  1433.2   234.8 1434.97   241.1 1437.54   244.7 1439.87   269.7 1458.35
#Mann= 4 ,-1 , 0
       0      .1       0   115.9    .045       0   144.5      .1       0
  213.94     .04       0
Bank Sta=115.9,144.5
XS Rating Curve= 0 ,0
Exp/Cntr(USF)=0,0
Exp/Cntr=0.3,0.1

Type RM Length L Ch R = 1 ,187     ,70.2,61.5,138.2
XS GIS Cut Line= 4
2028224.50728958219249.1042013532028323.69144631219311.094299305
2028398.47949996219307.4948742632028512.86122909219258.302732017
#Sta/Elev= 30
       0 1504.26     8.6 1502.91    17.4 1500.09    31.8 1493.56    43.4 1486.66
    47.3 1483.58      55 1473.24    58.9 1471.33    69.1 1470.47    73.9 1468.61
    79.3 1465.17    85.5 1459.99   101.4 1448.57   109.2 1444.65   116.7 1439.69
   123.5 1437.07   133.3 1428.91   143.2 1423.07   146.5 1421.95   159.6  1421.7
   162.9 1422.13   164.2 1423.11   169.5 1427.93   172.8 1430.18   182.6 1432.65
   213.9 1433.08   285.4 1438.89   292.2 1441.74   309.6 1456.63   316.3 1461.69
#Mann= 4 ,-1 , 0
       0      .1       0   143.2    .045       0   164.2      .1       0
  311.84     .04       0
Bank Sta=143.2,164.2
XS Rating Curve= 0 ,0
Exp/Cntr(USF)=0,0
Exp/Cntr=0.3,0.1

Type RM Length L Ch R = 1 ,125     ,56.4,56.4,56.4
XS GIS Cut Line= 4
2028209.49285824219307.3561934262028296.46671243219376.625219454
2028434.95751693219363.4684570492028550.26995674219266.174585386
#Sta/Elev= 30
       0 1461.25     5.6 1456.92    21.4 1454.13    39.3 1441.71      53 1434.25
    63.5 1427.79    68.8 1426.17      79 1424.74    90.7 1421.91   111.2  1421.3
   128.6 1421.73   155.31420.572   161.6 1420.03   184.4 1420.49   262.2 1421.01
   293.5 1424.99   306.4 1429.49   308.8 1429.85   321.8 1430.04   326.8 1430.68
   329.7  1432.3     337 1438.78     345  1444.2   352.3  1447.4   367.5 1450.59
   372.6 1452.78   387.9 1464.98   390.3 1465.88     393 1466.54   401.2 1466.24
#Mann= 6 ,-1 , 0
       0      .1       0      90    .025       0   155.3    .045       0
   184.4    .025       0   260.3      .1       0   390.3     .04       0
Bank Sta=155.3,184.4
XS Rating Curve= 0 ,0
Exp/Cntr(USF)=0,0
Exp/Cntr=0.3,0.1

Type RM Length L Ch R = 1 ,69      ,,,
XS GIS Cut Line= 4
 2028189.2037554219341.3262612662028226.88176557219447.419605704
2028520.86939759219403.7924360282028559.53893435219314.555043511
#Sta/Elev= 30
       0 1442.07     2.5 1440.85     5.9 1438.57     9.5 1435.59    12.9    1432
    16.4 1427.85    19.9 1425.57    23.3 1424.14      30 1423.08    33.8 1421.93
    37.7 1421.28    54.7 1421.67      79 1420.85    89.5 1420.86    94.2 1420.09
   106.9 1419.66   127.5 1419.69   170.5 1420.46   180.6 1420.05   197.1 1420.33
   213.3 1419.91   455.2 1420.43     461 1420.46   468.2 1420.99   471.8 1421.59
   474.9 1422.89   486.1  1430.2   492.7 1433.34   494.7 1434.58     507 1443.65
#Mann= 5 ,-1 , 0
       0      .1       0      20    .025       0    94.2    .045       0
   455.2    .025       0  459.79     .04       0
Bank Sta=94.2,455.2
XS Rating Curve= 0 ,0
Exp/Cntr(USF)=0,0
Exp/Cntr=0.3,0.1
LCMann Table=0

Chan Stop Cuts=-1
Use User Specified Reach Order=0
Composite Channel Slope=5